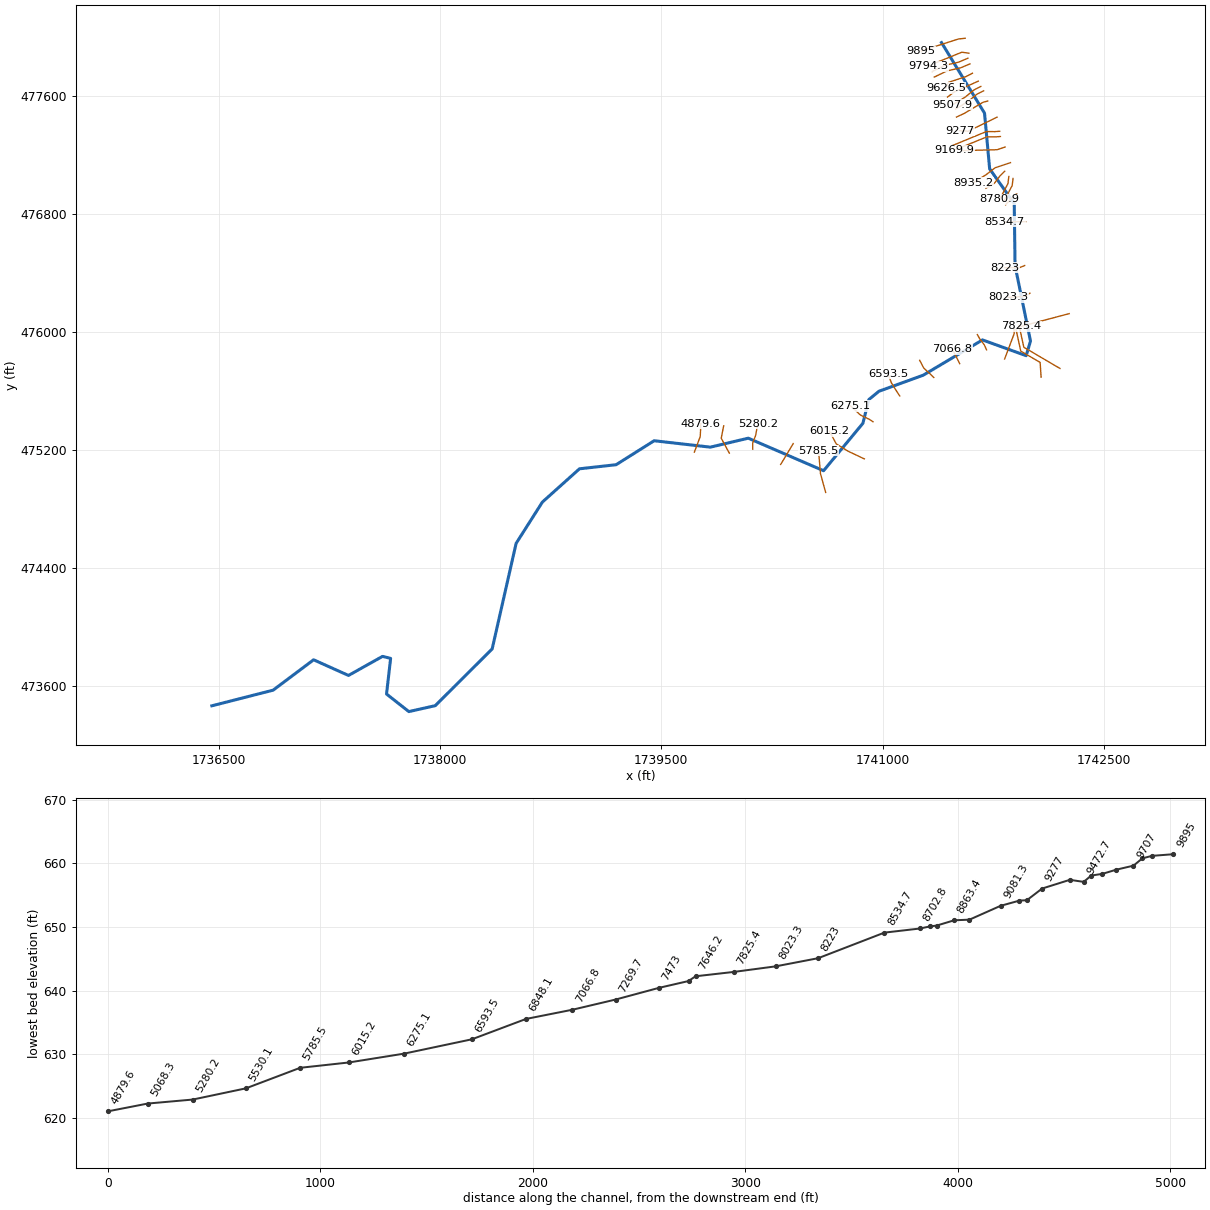
--- CROOKEDCK.prj (project) ---

Proj Title=CROOKEDCK
Current Plan=p01
Default Exp/Contr=0,0
English Units
Geom File=g01
Flow File=f01
Plan File=p01
BEGIN DESCRIPTION:
END DESCRIPTION:
DSS Export Rating Curves= 0
DSS Export Rating Curve Sorted= 0
DSS Export Volume Flow Curves= 0
DXF OffsetX= 0
DXF OffsetY= 0
DXF ScaleX= 0
DXF ScaleY= 0

--- CROOKEDCK.p01 (plan) ---

Plan Title=Floodplain
Program Version=4.00
Geom File=g01
Flow File=f01
K Sum by GR=0
Std Step Tol=0.01
Critical Tol=0.01
Num of Std Step Trials=20
Max Error Tol=0.3
Flow Tol Ratio=0.001
Split Flow NTrial=30
Split Flow Tol=0.02
Split Flow Ratio=0.02
Log Output Level=0
Friction Slope Method=1
Unsteady Friction Slope Method=2
Unsteady Bridges Friction Slope Method=1
Global Log Level=0
CheckData=False
Run HTab=0
Run UNet=0
Run PostProcess=0
UNET Theta=0
UNET Theta Warmup=0
UNET ZTol=0
UNET ZSATol=0
UNET MxIter=0
UNET MaxInSteps=0
UNET DtIC=0
UNET DtMin=0
UNET MaxCRTS=0
UNET WFStab=0
UNET SFStab=0
UNET WFX=0
UNET SFX=0
UNET DSS MLevel=0
UNET DZMax Abort=0
UNET Convert EG Bridges=0
UNET Use Existing IB Tables=0
UNET Froude Limit=0
UNET Froude Power=0
Write IC File=0
Echo Input=False
Echo Output=False
Write Detailed=0

--- CROOKEDCK.f01 (steady flow) ---

Flow Title=NFF Regression Equation
Program Version=4.10
Number of Profiles= 1
Profile Names=P100yr
River Rch & RM=CROOKEDCK,Main            ,9895
  997.75
River Rch & RM=CROOKEDCK,Main            ,7473
1080.162
River Rch & RM=CROOKEDCK,Main            ,1958.9
1323.617
River Rch & RM=CROOKEDCK,Main            ,458
1336.034
Boundary for River Rch & Prof#=CROOKEDCK,Main            , 1
Up Type= 0
Dn Type= 3
Dn Slope=0.002
DSS Import GetInterval= 0
DSS Import GetPeak= 0
DSS Import FillOption= 0

--- CROOKEDCK.g01 (geometry) ---

Geom Title=USGS 10m DEM
Program Version=4.10

River Reach=CROOKEDCK       ,Main
Reach XY= 30
     1741399.702      477962.276     1741691.349      477483.977
     1741726.071      477106.373     1741892.738      476871.998
     1741898.267      476450.972     1742002.981      475939.706
     1741973.467      475840.748      1741677.46      475947.518
     1741276.419      475708.803     1740975.203      475599.428
     1740906.627      475543.005     1740866.696      475382.414
     1740600.203      475061.234     1740089.787       475281.72
     1739832.842      475220.956     1739451.766      475264.359
     1739193.953      475102.032     1738945.689      475074.255
      1738694.16      474848.925     1738516.002      474569.046
     1738353.676      473853.768     1737967.845      473469.365
     1737788.808      473429.217      1737637.53      473548.213
     1737665.308      473789.532      1737610.62      473803.421
     1737379.717      473674.081     1737143.192      473780.231
     1736868.433      473574.255     1736453.502      473468.352

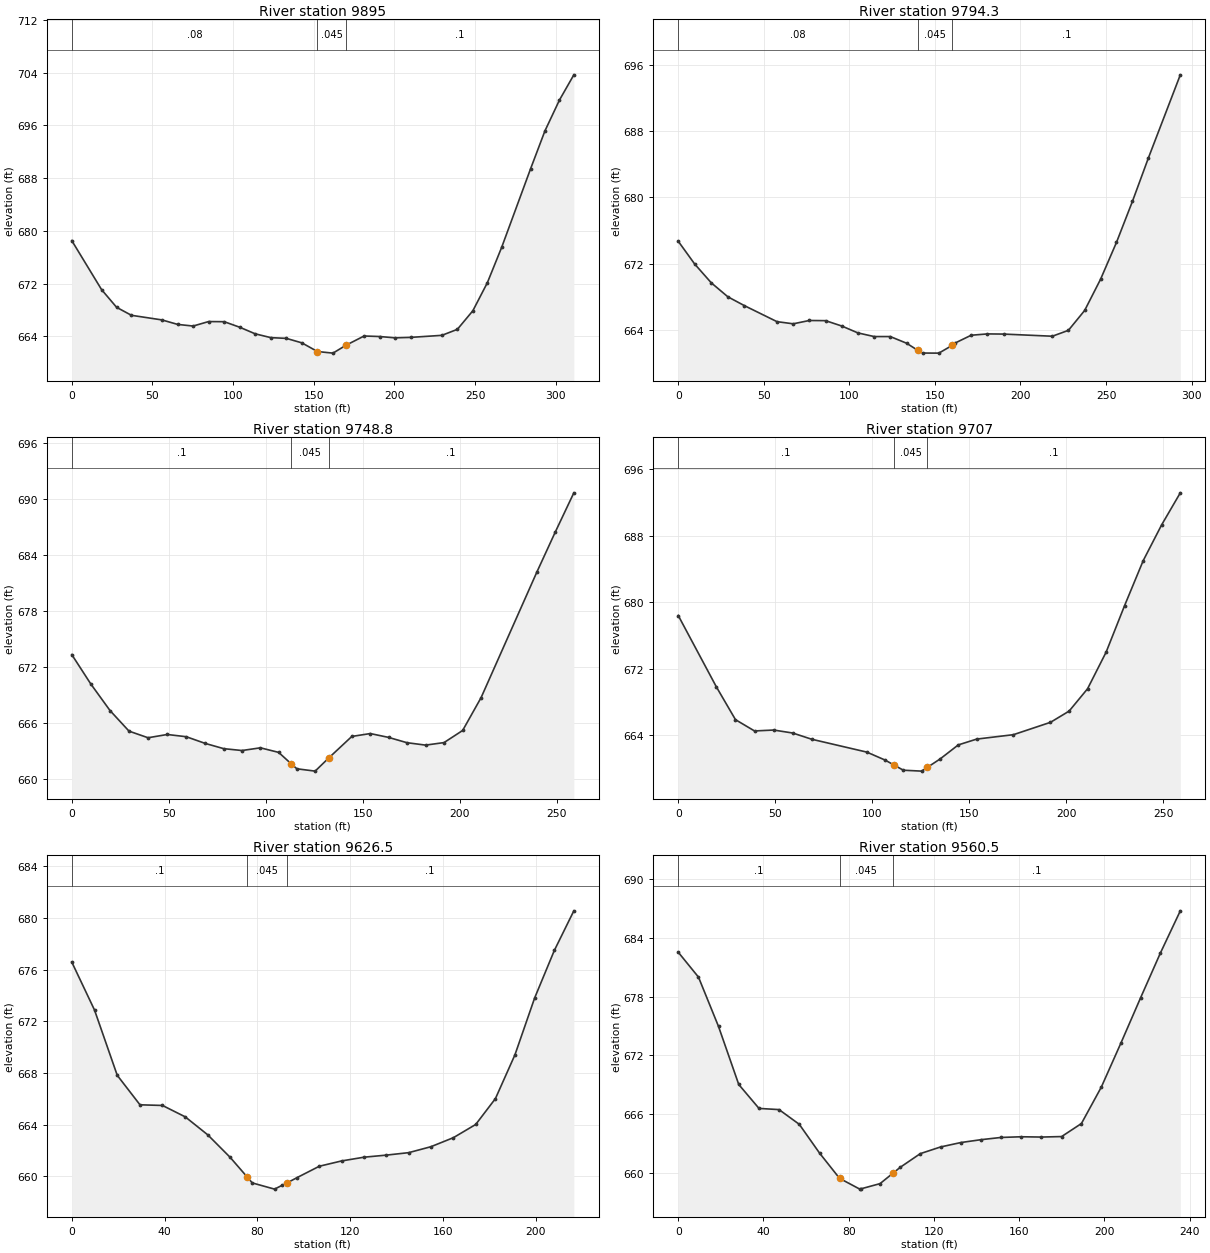
Type RM Length L Ch R = 1 ,9895    ,99,100.8,102.4
XS GIS Cut Line= 4
     1741560.128      477991.572     1741514.121      477986.364
     1741321.413      477924.732     1741262.385      477903.899
#Sta/Elev= 30
       0  678.53    18.5  671.08    27.8   668.4      37  667.19    55.9  666.49
    65.6  665.81    75.2  665.56    84.8  666.24    94.5  666.22   104.1  665.38
   113.7  664.38   123.4   663.8     133  663.69   142.6  663.01   152.3  661.69
   161.9  661.45     170  662.65   181.2  664.05   190.8  663.97   200.4  663.77
   210.1  663.84   229.4  664.15     239  665.06   248.6  667.88   257.6  672.14
   266.5  677.53   284.4  689.44   293.3  695.19   302.3  699.87   311.2  703.69
#Mann= 3 , 0 , 0
       0     .08       0   152.3    .045       0     170      .1       0
Bank Sta=152.3,170
XS Rating Curve= 0 ,0
Exp/Cntr=0.3,0.1

Type RM Length L Ch R = 1 ,9794.3  ,49.2,45.4,41.6
XS GIS Cut Line= 4
     1741585.302       477890.01     1741537.559      477896.954
     1741362.211      477825.774     1741311.864      477801.468
#Sta/Elev= 30
       0   674.7     9.6  671.95    19.3  669.68      29  667.99    38.6  666.93
    57.7  664.99    67.2  664.73    76.6  665.13    86.1  665.11    95.6  664.46
     105  663.63   114.5  663.19   123.9  663.19   133.4  662.39  140.04  661.52
   142.9   661.2   152.3  661.19  160.23  662.14   161.8  662.41   171.2  663.35
   180.7  663.51   190.2  663.49   218.6  663.23     228  663.94   237.5  666.34
   246.8  670.11   256.1  674.56   265.4   679.5   274.8  684.78   293.4  694.79
#Mann= 3 , 0 , 0
       0     .08       0  140.04    .045       0  160.23      .1       0
Bank Sta=140.04,160.23
XS Rating Curve= 0 ,0
Exp/Cntr=0.3,0.1

Type RM Length L Ch R = 1 ,9748.8  ,42.9,41.8,41.8
XS GIS Cut Line= 4
     1741578.357      477856.156     1741514.989      477829.246
     1741422.975      477808.413     1741337.038      477766.746
#Sta/Elev= 27
       0   673.3     9.8  670.15    19.7   667.3    29.5  665.09    39.3  664.38
    49.2  664.73      59  664.49    68.8  663.77    78.3  663.21    87.7  663.01
    97.2   663.3   106.6  662.81   113.2  661.56     116  661.05   125.4   660.8
   132.3  662.19   144.3  664.52   153.8  664.83   163.2  664.42   172.7  663.85
   182.3  663.59   191.8  663.86   201.4  665.16   210.9  668.68   239.6  682.13
   249.1  686.43   258.7  690.65
#Mann= 3 , 0 , 0
       0      .1       0   113.2    .045       0   132.3      .1       0
Bank Sta=113.2,132.3
XS Rating Curve= 0 ,0
Exp/Cntr=0.3,0.1

Type RM Length L Ch R = 1 ,9707    ,76.9,80.5,82.4
XS GIS Cut Line= 4
     1741592.246      477817.961     1741528.878      477791.051
     1741436.864      477770.218     1741350.927      477728.551
#Sta/Elev= 25
       0   678.4    19.7  669.78    29.5  665.85    39.3  664.49    49.2   664.6
      59  664.24    68.8  663.49    97.2  661.94   106.6  660.98   111.3  660.37
     116  659.76   125.4  659.65  128.34   660.1   134.9  661.11   144.3  662.81
   153.8  663.51   172.7  664.04   191.8  665.53   201.4  666.88   210.9  669.57
   220.5     674     230   679.6   239.6  685.02   249.1  689.33   258.7  693.18
#Mann= 3 , 0 , 0
       0      .1       0   111.3    .045       0  128.34      .1       0
Bank Sta=111.3,128.34
XS Rating Curve= 0 ,0
Exp/Cntr=0.3,0.1

Type RM Length L Ch R = 1 ,9626.5  ,63.7,66,68.7
XS GIS Cut Line= 4
     1741609.607      477754.593     1741566.205      477732.024
     1741447.281      477692.961     1741429.052      477654.767
#Sta/Elev= 27
       0  676.58     9.8  672.87    19.6  667.82    29.4  665.54    39.1  665.49
    48.9  664.61    58.6  663.22    68.2  661.49    75.6  659.96    77.8   659.5
    87.4  659.02    90.6  659.31   92.56  659.48    97.1  659.91   106.7  660.79
   116.3   661.2     126  661.49   135.6  661.65   145.2  661.84   154.8   662.3
   164.5     663   174.1  664.02   182.6  666.02     191   669.4   199.5   673.8
     208  677.48   216.4  680.54
#Mann= 3 , 0 , 0
       0      .1       0    75.6    .045       0   92.56      .1       0
Bank Sta=75.6,92.56
XS Rating Curve= 0 ,0
Exp/Cntr=0.3,0.1

Type RM Length L Ch R = 1 ,9560.5  ,46.6,52.6,58.6
XS GIS Cut Line= 3
      1741648.67      477700.774     1741484.607      477626.989
     1741440.336      477593.135
#Sta/Elev= 28
       0  682.52     9.5  679.98    18.9  674.95    28.4  669.03    37.9  666.59
    47.3  666.47    56.8  664.97    66.3  662.04    75.7  659.46    85.2  658.36
    85.9   658.4    94.7  658.92   100.9  660.01   104.2  660.59   113.6  661.98
   123.1  662.66   132.6  663.11     142   663.4   151.5  663.63     161   663.7
   170.4  663.67   179.9  663.72   189.2  665.05   198.5  668.75   207.8  673.29
     217  677.89   226.3  682.46   235.6  686.74
#Mann= 3 , 0 , 0
       0      .1       0    75.7    .045       0   100.9      .1       0
Bank Sta=75.7,100.9
XS Rating Curve= 0 ,0
Exp/Cntr=0.3,0.1

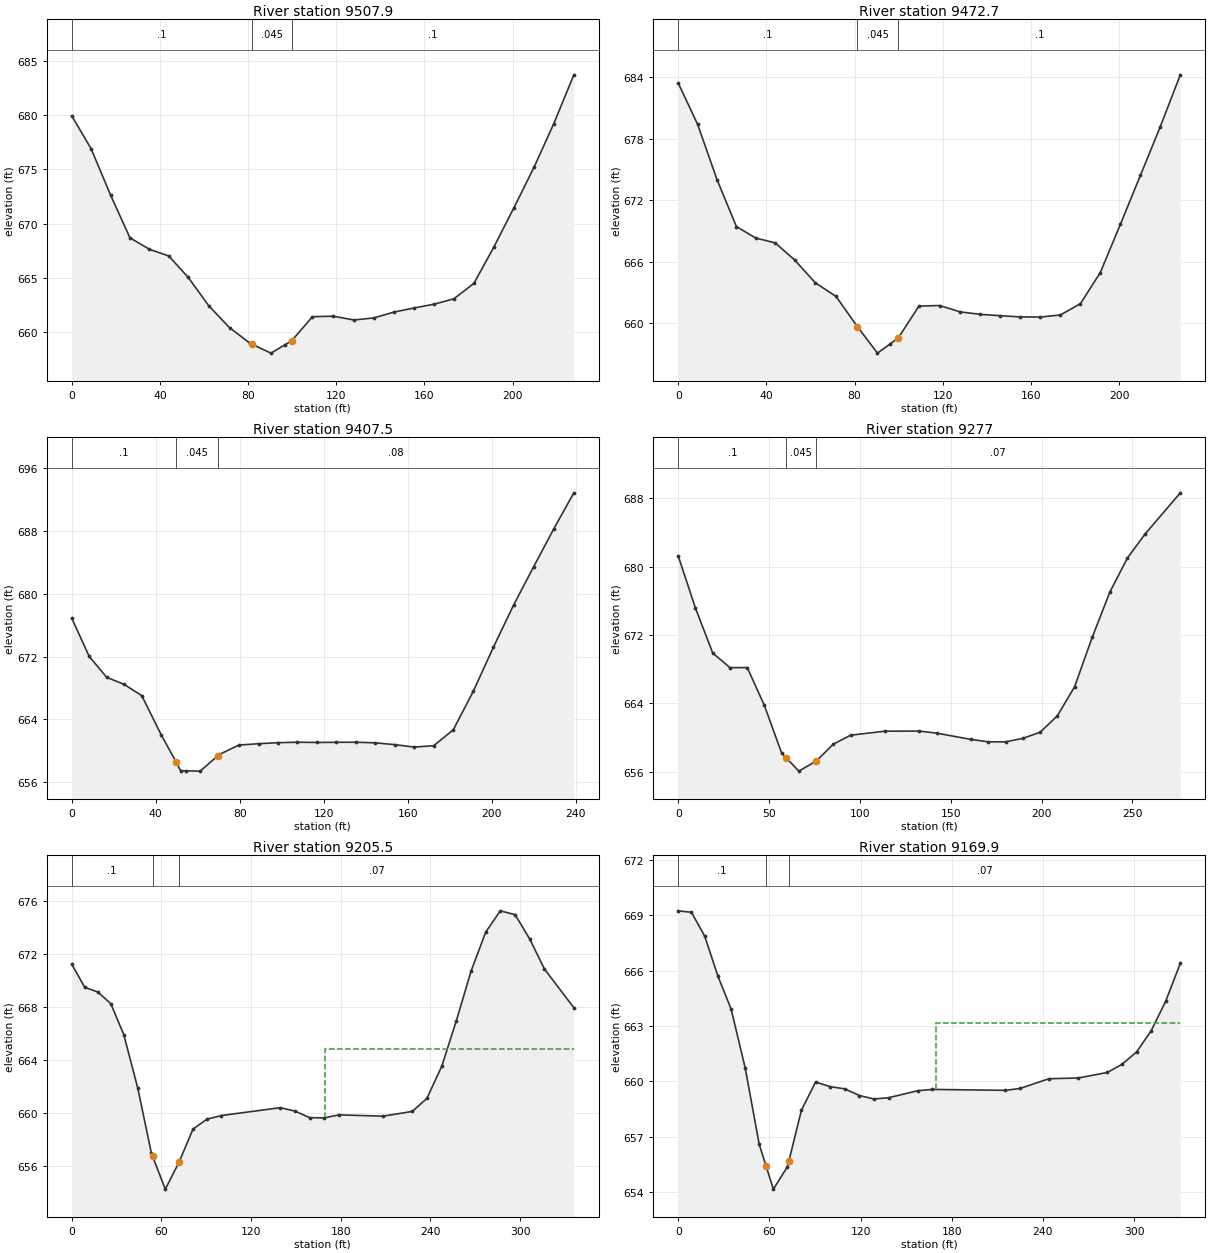
Type RM Length L Ch R = 1 ,9507.9  ,35.3,35.2,35.1
XS GIS Cut Line= 4
     1741666.031      477665.183     1741619.156      477640.878
     1741560.996      477593.135     1741475.927      477541.051
#Sta/Elev= 28
       0  679.92     8.8  676.89    17.6  672.64    26.4   668.7    35.2  667.65
      44  667.03    52.8  665.07    62.2  662.44    71.6  660.43      81  658.98
    81.8   658.9    90.4  658.09    96.8  658.87    99.8  659.23   109.2  661.44
   118.6  661.49     128  661.14   137.1  661.33   146.2  661.87   155.2  662.24
   164.3  662.59   173.4  663.09   182.5  664.52   191.5  667.85   200.6  671.46
   209.7  675.18   218.7  679.21   227.8   683.7
#Mann= 3 , 0 , 0
       0      .1       0    81.8    .045       0    99.8      .1       0
Bank Sta=81.8,99.8
XS Rating Curve= 0 ,0
Exp/Cntr=0.3,0.1

Type RM Length L Ch R = 1 ,9472.7  ,68.5,65.3,61.8
XS GIS Cut Line= 4
     1741685.128      477635.669     1741638.253      477611.364
     1741580.093      477563.621     1741495.024      477511.538
#Sta/Elev= 28
       0  683.43     8.8  679.41    17.6  674.02    26.4  669.44    35.2  668.32
      44  667.85    52.8  666.19    62.2  663.96    71.6  662.63      81  659.77
    81.3  659.68    90.4   657.1    96.3  658.02    99.8  658.56   109.2  661.69
   118.6  661.74     128  661.12   137.1  660.88   146.2  660.75   155.2  660.63
   164.3  660.62   173.4  660.82   182.5  661.93   191.5  664.96   200.6  669.66
   209.7  674.43   218.7  679.18   227.8  684.24
#Mann= 3 , 0 , 0
       0      .1       0    81.3    .045       0    99.8      .1       0
Bank Sta=81.3,99.8
XS Rating Curve= 0 ,0
Exp/Cntr=0.3,0.1

Type RM Length L Ch R = 1 ,9407.5  ,132.3,130.4,128.7
XS GIS Cut Line= 4
     1741712.906      477566.225     1741680.788      477557.544
     1741553.184      477482.024       1741501.1      477457.718
#Sta/Elev= 30
       0  676.88     8.3  672.03    16.6  669.37      25  668.45    33.3  667.04
    42.5  662.08    49.6  658.62    51.8  657.47    54.4  657.46    61.1  657.42
    69.4  659.34    70.3  659.55    79.6  660.74    88.9  660.91    98.1  661.04
   107.4   661.1   116.7  661.07   125.9  661.09   135.2   661.1   144.5  661.02
   153.8  660.79     163  660.48   172.3  660.66   181.6  662.68   191.1  667.57
   200.7  673.19   210.3  678.55   219.9  683.46   229.4  688.24     239  692.85
#Mann= 3 , 0 , 0
       0      .1       0    49.6    .045       0    69.4     .08       0
Bank Sta=49.6,69.4
XS Rating Curve= 0 ,0
Exp/Cntr=0.3,0.1

Type RM Length L Ch R = 1 ,9277    ,82.2,71.6,60.9
XS GIS Cut Line= 3
     1741776.274       477456.85     1741580.093      477361.364
     1741521.934      477364.836
#Sta/Elev= 27
       0  681.24     9.5  675.14      19  669.88    28.5  668.17      38  668.18
    47.4  663.76    56.9  658.18    59.6  657.57    66.4  656.05    75.9  657.22
    85.4  659.21    94.9  660.26   113.8  660.73   132.8  660.74   142.3   660.5
   161.3  659.76   170.8  659.48   180.2  659.48   189.7  659.89   199.2   660.6
   208.7  662.52   218.2  665.93   227.9  671.72   237.6  677.02   247.3  681.02
     257  683.82   276.4  688.65
#Mann= 3 , 0 , 0
       0      .1       0    59.6    .045       0    75.9     .07       0
Bank Sta=59.6,75.9
XS Rating Curve= 0 ,0
Exp/Cntr=0.3,0.1

Type RM Length L Ch R = 1 ,9205.5  ,35.5,35.6,35.5
XS GIS Cut Line= 4
     1741794.503      477361.364     1741759.781       477358.76
     1741704.225      477359.628     1741477.227       477265.89
#Sta/Elev= 30
       0  671.21     8.7  669.46    17.4  669.11    26.1  668.23    34.8  665.89
    44.1  661.88    53.3  656.92    54.1  656.69    62.6  654.22    71.9  656.28
    81.1  658.75    90.4   659.5   100.2  659.78   139.5  660.37   149.3  660.12
   159.2  659.62     169   659.6   178.8  659.83   208.3  659.73   227.9  660.09
   237.7  661.08   247.6   663.5   257.4  666.95   267.2  670.68     277  673.63
   286.8  675.24   296.7  674.95   306.5  673.11   316.3  670.85     336  667.92
#Mann= 3 , 0 , 0
       0      .1       0    54.1    .045       0    71.9     .07       0
#XS Ineff= 2 , 0
                          169.57          664.81
Permanent Ineff=
       F       F
Bank Sta=54.1,71.9
XS Rating Curve= 0 ,0
Exp/Cntr=0.3,0.1

Type RM Length L Ch R = 1 ,9169.9  ,87.7,88.6,89.6
XS GIS Cut Line= 4
     1741798.843      477325.774     1741764.121      477323.169
     1741708.566      477324.038     1741486.342      477233.338
#Sta/Elev= 30
       0  669.25     8.7  669.17    17.4  667.88    26.1  665.71    34.8  663.92
    44.1  660.71    53.3  656.58    57.8   655.4    62.6  654.15    71.9  655.37
    72.8  655.67    81.1  658.44    90.4  659.96     100  659.71   109.6  659.59
   119.2  659.23   128.8  659.04   138.4  659.11   157.6  659.49   167.2  659.56
   215.2  659.51   224.8  659.61     244  660.14   263.2  660.18   282.4  660.48
     292  660.92   301.6  661.59   311.2  662.74   320.8  664.35   330.4   666.4
#Mann= 3 , 0 , 0
       0      .1       0    57.8    .045       0    72.8     .07       0
#XS Ineff= 2 , 0
                          169.88          663.14
Permanent Ineff=
       F       F
Bank Sta=57.8,72.8
XS Rating Curve= 0 ,0
Exp/Cntr=0.3,0.1

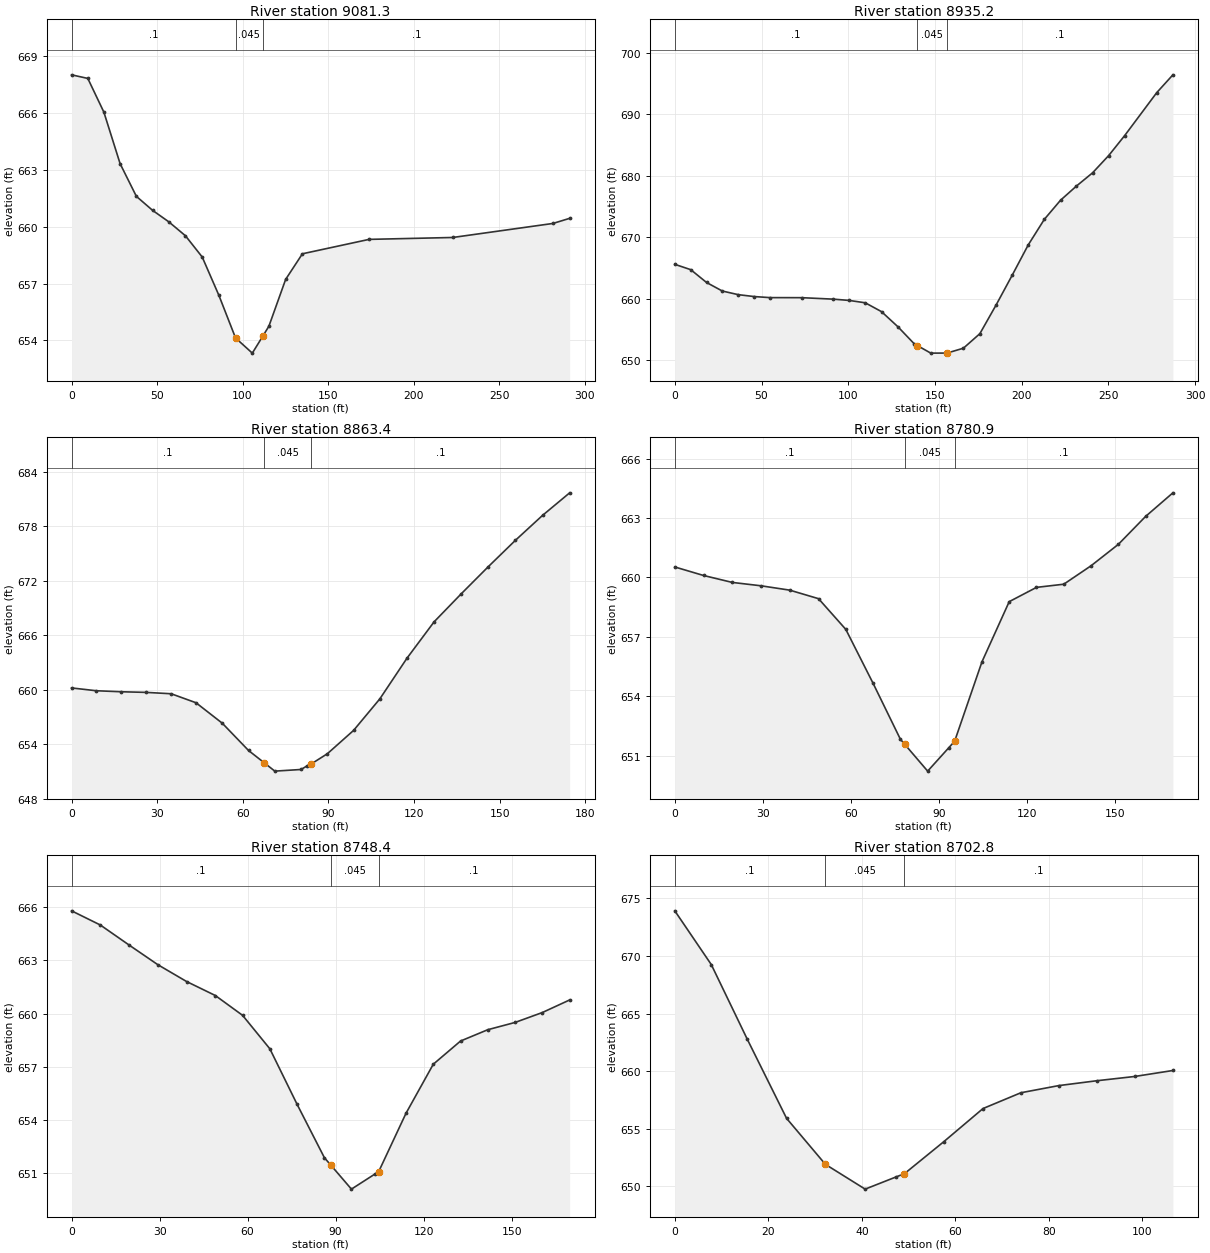
Type RM Length L Ch R = 1 ,9081.3  ,131.6,146.1,160.3
XS GIS Cut Line= 3
     1741830.961      477254.593     1741777.142      477236.364
     1741542.767      477230.288
#Sta/Elev= 20
       0  668.01     9.5  667.82    18.9  666.04    28.4  663.32    37.9   661.6
    47.4  660.86    56.8  660.26    66.6  659.52    76.4   658.4    86.1  656.39
    95.9  654.13   105.7  653.33     112  654.25   115.4  654.75   125.2  657.22
     135  658.57     174  659.33   222.9  659.43   281.5  660.17   291.3  660.44
#Mann= 3 , 0 , 0
       0      .1       0    95.9    .045       0     112      .1       0
Bank Sta=95.9,112
XS Rating Curve= 0 ,0
Exp/Cntr=0.3,0.1

Type RM Length L Ch R = 1 ,8935.2  ,65.9,71.8,77.7
XS GIS Cut Line= 4
      1741867.42       477148.69     1741763.253      477113.968
     1741703.357      477067.961      1741617.42      477013.274
#Sta/Elev= 30
       0  665.59     9.2  664.72    18.3  662.64    27.4  661.25    36.6  660.66
    45.8  660.35    54.9  660.18    73.2  660.17    91.5  659.93   100.6  659.72
   109.8  659.34   119.2   657.9   128.7  655.43   138.1  652.66   139.9  652.38
   147.6  651.16     157  651.17   166.4  651.96   175.9  654.32   185.3     659
   194.6  663.85   203.8  668.75   213.1  672.91   222.4     676   231.6  678.31
   240.9  680.46   250.2  683.27   259.4  686.51   277.9  693.49   287.2  696.38
#Mann= 3 , 0 , 0
       0      .1       0   139.9    .045       0     157      .1       0
Bank Sta=139.9,157
XS Rating Curve= 0 ,0
Exp/Cntr=0.3,0.1

Type RM Length L Ch R = 1 ,8863.4  ,78.7,82.5,86.4
XS GIS Cut Line= 4
     1741828.357      477090.531     1741797.107      477060.149
     1741758.045      477008.933     1741700.753      476975.079
#Sta/Elev= 23
       0  660.21     8.7   659.9    17.4  659.79    26.2  659.72    34.9  659.57
    43.6  658.58    52.8  656.33      62  653.33    67.4     652    71.2  651.06
    80.4  651.24    82.4  651.62   83.86  651.83    89.6  652.97    98.8  655.54
     108  659.01   117.5  663.48     127  667.48   136.5  670.56     146  673.55
   155.5  676.45     165  679.19   174.5  681.67
#Mann= 3 , 0 , 0
       0      .1       0    67.4    .045       0   83.86      .1       0
Bank Sta=67.4,83.86
XS Rating Curve= 0 ,0
Exp/Cntr=0.3,0.1

Type RM Length L Ch R = 1 ,8780.9  ,32.4,32.4,33.4
XS GIS Cut Line= 3
     1741856.135       477054.94     1741850.059      477006.329
     1741793.635      476899.558
#Sta/Elev= 21
       0  660.53     9.8   660.1    19.6  659.75    29.4  659.58    39.2  659.36
      49  658.93    58.3  657.38    67.6  654.66    76.9  651.84    78.4  651.58
    86.2  650.23    93.4  651.41    95.4  651.74   104.7  655.74     114  658.78
   123.3   659.5   132.6  659.66   141.9  660.59   151.2  661.67   160.5  663.08
   169.8  664.27
#Mann= 3 , 0 , 0
       0      .1       0    78.4    .045       0    95.4      .1       0
Bank Sta=78.4,95.4
XS Rating Curve= 0 ,0
Exp/Cntr=0.3,0.1

Type RM Length L Ch R = 1 ,8748.4  ,51.8,45.7,39.2
XS GIS Cut Line= 3
     1741884.781      477041.919     1741878.705      476993.308
     1741822.281      476886.538
#Sta/Elev= 21
       0   665.8     9.8     665    19.6  663.87    29.4  662.76    39.2  661.81
      49  661.02    58.3   659.9    67.6  658.01    76.9  654.87    86.2  651.86
    88.3  651.46    95.4  650.09   103.3  650.93   104.7  651.08     114  654.37
   123.3  657.14   132.6  658.45   141.9  659.09   151.2   659.5   160.5  660.06
   169.8  660.77
#Mann= 3 , 0 , 0
       0      .1       0    88.3    .045       0   104.7      .1       0
Bank Sta=88.3,104.7
XS Rating Curve= 0 ,0
Exp/Cntr=0.3,0.1

Type RM Length L Ch R = 1 ,8702.8  ,186.4,168,149.1
XS GIS Cut Line= 4
     1741909.955      476936.885     1741896.066       476929.94
     1741861.343      476893.482     1741834.434        476863.1
#Sta/Elev= 15
       0  673.91     7.8  669.25    15.5  662.77    23.9  655.91    32.2  651.92
    40.7  649.77    47.2  650.81    49.1  651.11    57.5  653.88    65.9  656.76
      74  658.13    82.1  658.75    90.2  659.17    98.3  659.54   106.5  660.06
#Mann= 3 , 0 , 0
       0      .1       0    32.2    .045       0    49.1      .1       0
Bank Sta=32.2,49.1
XS Rating Curve= 0 ,0
Exp/Cntr=0.3,0.1

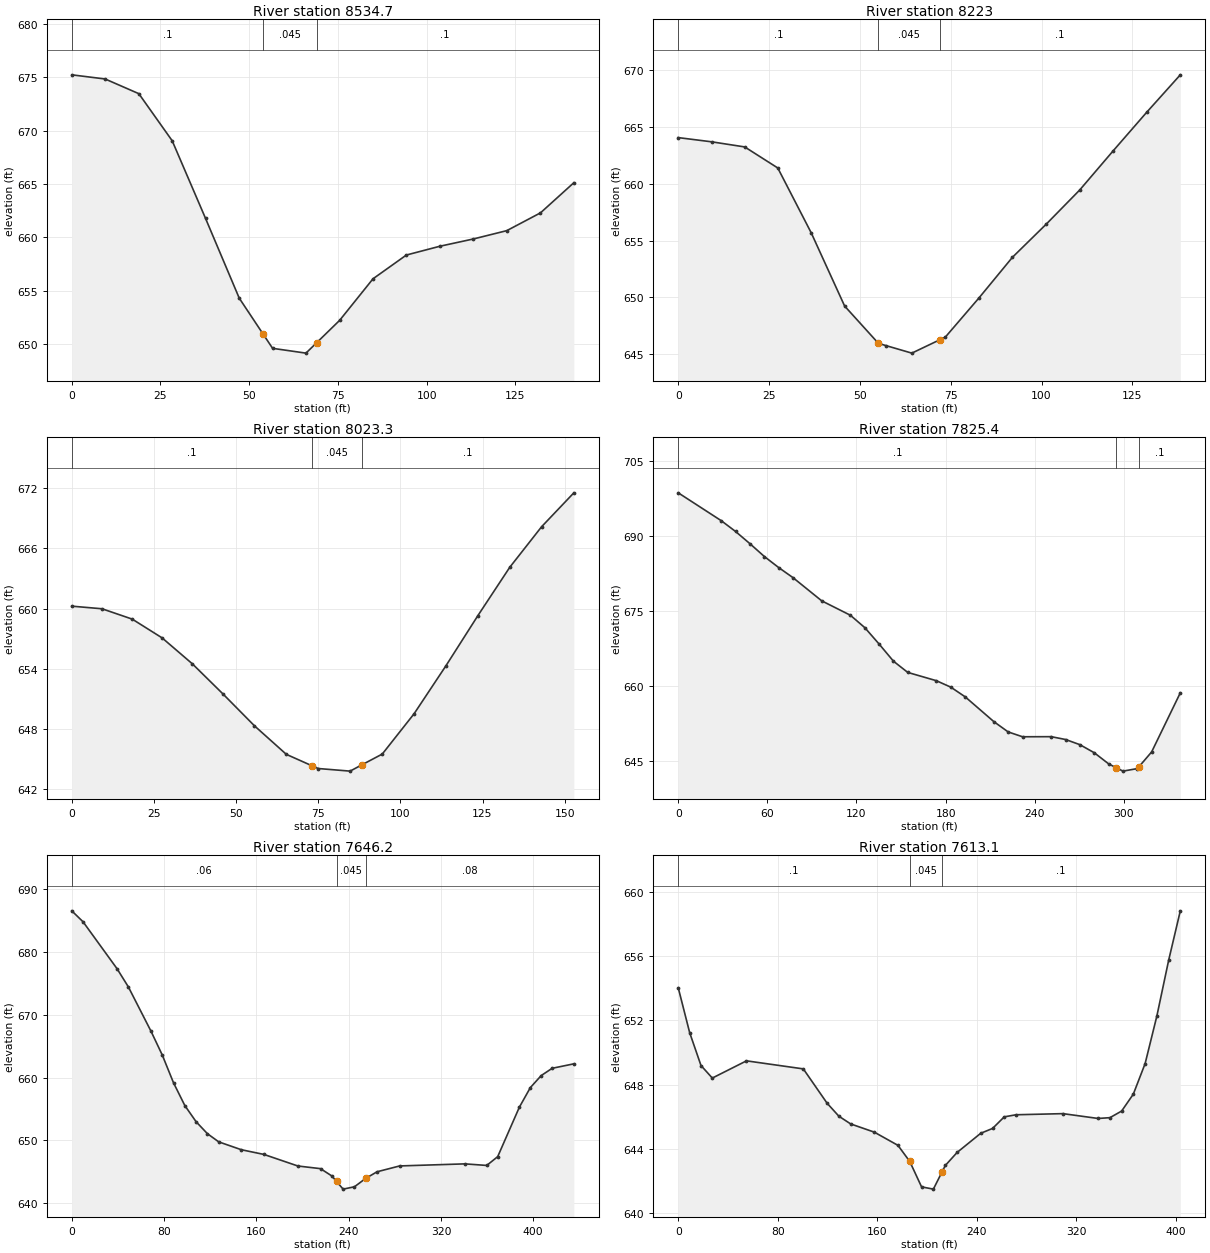
Type RM Length L Ch R = 1 ,8534.7  ,311.5,311.7,311.5
XS GIS Cut Line= 2
     1741970.718      476748.517     1741829.225      476747.649
#Sta/Elev= 18
       0  675.25     9.4  674.86    18.9  673.48    28.3  669.06    37.7  661.77
    47.2  654.28      54  650.87    56.6  649.57      66  649.12      69  650.09
    75.5   652.2    84.9   656.1    94.3  658.33   103.8  659.16   113.2  659.84
   122.6  660.62   132.1  662.29   141.5  665.12
#Mann= 3 , 0 , 0
       0      .1       0      54    .045       0      69      .1       0
Bank Sta=54,69
XS Rating Curve= 0 ,0
Exp/Cntr=0.3,0.1

Type RM Length L Ch R = 1 ,8223    ,198.7,199.7,200.6
XS GIS Cut Line= 3
     1741963.774      476451.642      1741929.92      476437.753
     1741828.357      476436.885
#Sta/Elev= 18
       0  664.05     9.2  663.68    18.3  663.23    27.4  661.38    36.6  655.68
    45.8  649.24    55.1  645.96    57.1  645.77    64.3   645.1    72.1  646.29
    73.5   646.5    82.8  649.96      92  653.53   101.2  656.41   110.5  659.44
   119.7  662.88   128.9  666.26   138.2  669.57
#Mann= 3 , 0 , 0
       0      .1       0    55.1    .045       0    72.1      .1       0
Bank Sta=55.1,72.1
XS Rating Curve= 0 ,0
Exp/Cntr=0.3,0.1

Type RM Length L Ch R = 1 ,8023.3  ,193.1,197.9,202.6
XS GIS Cut Line= 3
     1741999.364      476264.142     1741959.434      476241.572
     1741852.663      476236.364
#Sta/Elev= 19
       0  660.24     9.2  659.98    18.4  658.95    27.5  657.08    36.7   654.5
    45.9  651.54    55.6  648.33    65.3  645.49    73.2  644.34      75  644.08
    84.7  643.82    88.2  644.43    94.5  645.52   104.2  649.54   113.9  654.32
   123.6   659.3   133.3  664.11     143  668.15   152.8  671.52
#Mann= 3 , 0 , 0
       0      .1       0    73.2    .045       0    88.2      .1       0
Bank Sta=73.2,88.2
XS Rating Curve= 0 ,0
Exp/Cntr=0.3,0.1

Type RM Length L Ch R = 1 ,7825.4  ,197.3,179.2,160.7
XS GIS Cut Line= 2
     1742265.422      476125.699       1741938.6      476039.315
#Sta/Elev= 30
       0  698.59      29  693.01    38.6  690.86    48.3  688.41      58  685.85
    67.6  683.65    77.3  681.62    96.6  676.99   115.9  674.11   125.6  671.63
   135.2  668.36   144.9  664.92   154.5  662.68   173.8  661.02   183.5  659.73
   193.2  657.79   212.5  652.83   222.1  650.78   231.8  649.81   251.1  649.83
   260.8  649.26   270.4  648.23   280.1  646.61   289.8  644.38     295   643.6
   299.4  642.94   309.1  643.45     310  643.76   318.7  646.78     338   658.6
#Mann= 3 , 0 , 0
       0      .1       0     295    .045       0     310      .1       0
Bank Sta=295,310
XS Rating Curve= 0 ,0
Exp/Cntr=0.3,0.1

Type RM Length L Ch R = 1 ,7646.2  ,33.1,33.1,46.7
XS GIS Cut Line= 3
     1742202.922      475754.171     1741957.698      475897.822
      1741925.58      476045.392
#Sta/Elev= 30
       0  686.55     9.8   684.8    39.2  677.35      49  674.46    68.6  667.42
    78.4  663.62    88.2  659.18      98  655.56   107.8  652.98   117.6  651.08
   127.4  649.78     147  648.53   166.6  647.78     196  645.94   215.6  645.52
   225.4  644.36   229.5  643.48   235.2  642.26     245  642.63   254.8  643.97
   264.6  645.02   284.2  645.95   340.8  646.28   359.7  646.03   369.2  647.43
     388  655.31   397.5  658.42   406.9  660.33   416.4  661.49   435.2   662.2
#Mann= 3 , 0 , 0
       0     .06       0   229.5    .045       0   254.8     .08       0
Bank Sta=229.5,254.8
XS Rating Curve= 0 ,0
Exp/Cntr=0.3,0.1

Type RM Length L Ch R = 1 ,7613.1  ,173.6,140.1,92.8
XS GIS Cut Line= 4
     1742074.885      475694.697     1742068.287      475795.117
     1741936.864      475871.781     1741904.746       476019.35
#Sta/Elev= 30
       0  654.02     9.2  651.23    18.3  649.19    27.4  648.41    54.9  649.48
   100.6  648.98   119.7  646.85   129.2  646.04   138.7  645.56   157.7  645.05
   176.7  644.23   186.2  643.23   195.7  641.65   205.2  641.51   212.1  642.57
   214.8  642.98   224.3  643.79   243.3  644.98   252.8  645.28   262.2     646
   271.7  646.13   309.4   646.2   337.7   645.9   347.2  645.95   356.6  646.36
     366  647.41   375.5  649.31   384.9  652.25   394.4  655.72   403.8   658.8
#Mann= 3 , 0 , 0
       0      .1       0   186.2    .045       0   212.1      .1       0
Bank Sta=186.2,212.1
XS Rating Curve= 0 ,0
Exp/Cntr=0.3,0.1

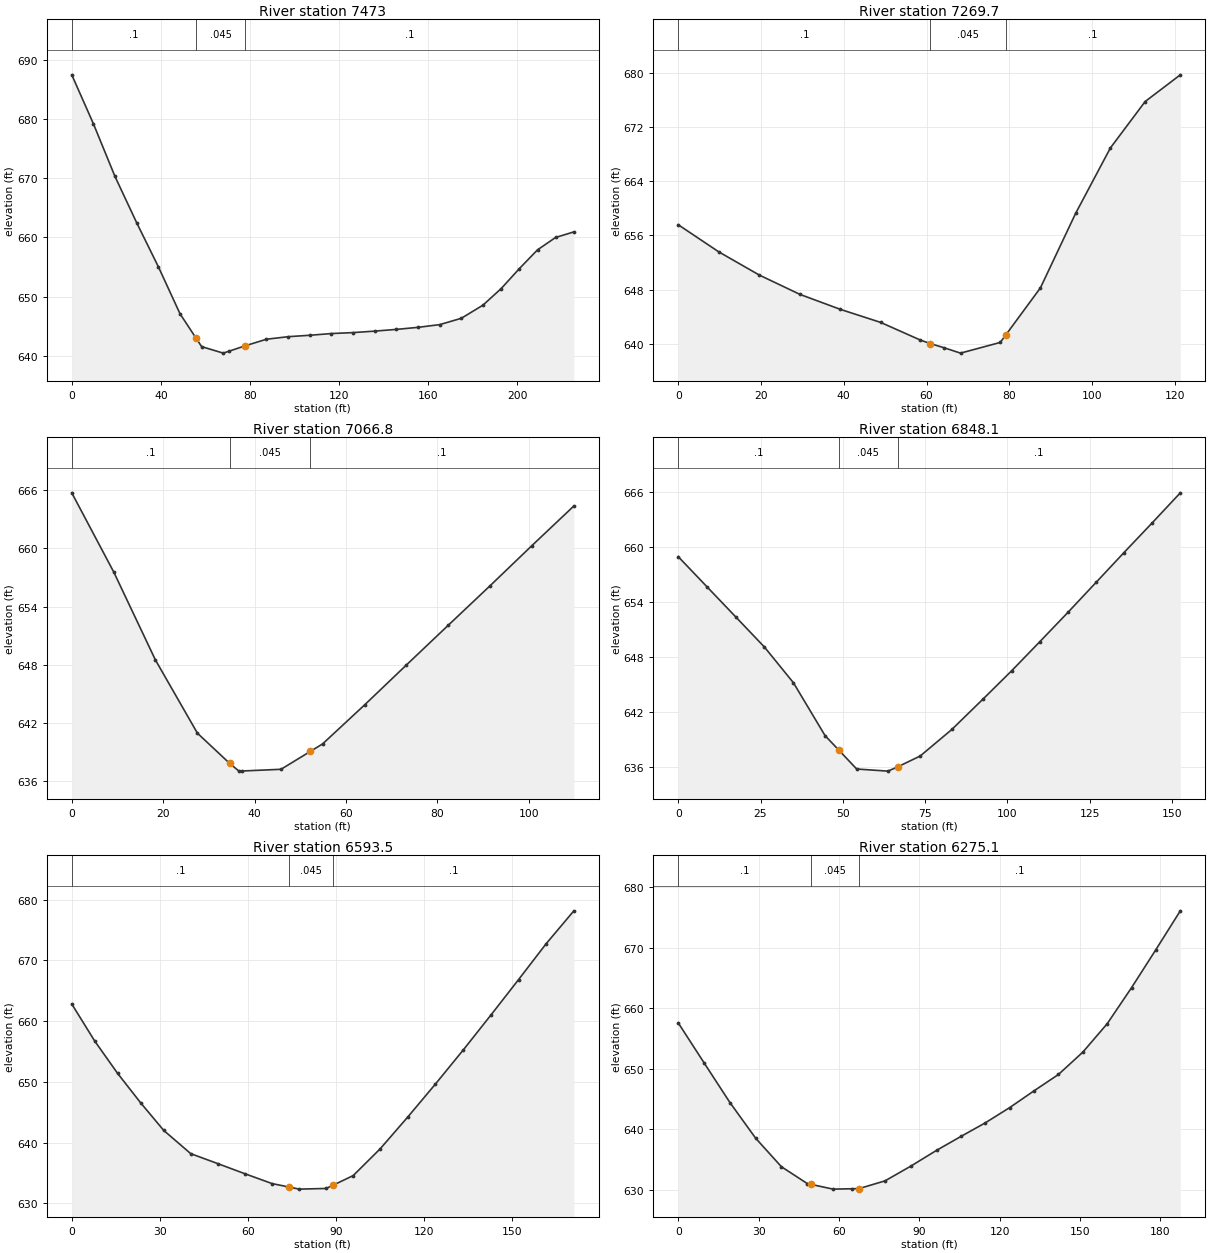
Type RM Length L Ch R = 1 ,7473    ,179.8,203.3,225.3
XS GIS Cut Line= 3
     1741827.489      475817.961     1741892.593      475990.704
     1741891.725      476031.503
#Sta/Elev= 27
       0  687.47     9.7  679.21    19.4  670.29    29.2  662.42    38.9  655.01
    48.6  647.08    55.8  642.96    58.3  641.53      68  640.43    70.8  640.78
    77.7  641.65    87.4  642.78    97.2  643.21   106.9  643.45   116.6  643.74
   126.3   643.9     136  644.15   145.7  644.44   155.5  644.79   165.2  645.25
   174.9  646.32   184.6  648.54   192.8  651.35   200.9   654.7   209.1  657.89
   217.2  659.98   225.4  660.92
#Mann= 3 , 0 , 0
       0      .1       0    55.8    .045       0    77.7      .1       0
Bank Sta=55.8,77.7
XS Rating Curve= 0 ,0
Exp/Cntr=0.3,0.1

Type RM Length L Ch R = 1 ,7269.7  ,207,202.9,199.3
XS GIS Cut Line= 4
     1741705.093      475880.461       1741688.6      475916.051
     1741659.086      475954.246     1741642.593       475983.76
#Sta/Elev= 17
       0  657.57     9.8  653.56    19.6  650.13    29.4  647.28    39.2  645.06
    48.9  643.14    58.5  640.53   60.89  640.01    64.2   639.4    68.2   638.6
    77.8  640.18    79.2  641.34    87.5  648.24      96  659.24   104.4  668.91
   112.8  675.77   121.3  679.72
#Mann= 3 , 0 , 0
       0      .1       0   60.89    .045       0    79.2      .1       0
Bank Sta=60.89,79.2
XS Rating Curve= 0 ,0
Exp/Cntr=0.3,0.1

Type RM Length L Ch R = 1 ,7066.8  ,210.4,218.7,226.9
XS GIS Cut Line= 2
     1741522.802      475786.711     1741473.323      475884.801
#Sta/Elev= 16
       0  665.74     9.2  657.55    18.3  648.49    27.5  640.92   34.54  637.81
    36.6     637    37.2  637.01    45.8  637.19    52.2  639.03    54.9  639.81
    64.1  643.84    73.2  647.94    82.4  652.06    91.6  656.16   100.7  660.28
   109.9  664.38
#Mann= 3 , 0 , 0
       0      .1       0   34.54    .045       0    52.2      .1       0
Bank Sta=34.54,52.2
XS Rating Curve= 0 ,0
Exp/Cntr=0.3,0.1

Type RM Length L Ch R = 1 ,6848.1  ,260.6,254.6,248.4
XS GIS Cut Line= 4
     1741347.455      475692.961     1741322.281      475717.267
     1741279.746      475756.329     1741251.968      475809.281
#Sta/Elev= 20
       0  658.93     8.8  655.62    17.5  652.35    26.2  649.07      35  645.18
    44.6  639.42    48.7  637.87    54.2  635.78    63.7  635.55   66.75  636.03
    73.5   637.2    83.1  640.09    92.7  643.45   101.3   646.5   109.8  649.65
   118.4  652.87   126.9  656.12   135.4  659.38     144  662.63   152.5  665.89
#Mann= 3 , 0 , 0
       0      .1       0    48.7    .045       0   66.75      .1       0
Bank Sta=48.7,66.75
XS Rating Curve= 0 ,0
Exp/Cntr=0.3,0.1

Type RM Length L Ch R = 1 ,6593.5  ,305.3,318.4,330.5
XS GIS Cut Line= 4
     1741116.552      475567.961     1741099.191      475594.003
     1741060.128      475656.503     1741036.691      475718.135
#Sta/Elev= 22
       0  662.83     7.8  656.74    15.6  651.41    23.5  646.53    31.3  642.02
    40.5  638.19    49.7  636.55    58.9  634.89    68.2  633.26      74  632.69
    77.4  632.35    86.6  632.46      89  633.01    95.8  634.58     105     639
   114.4  644.24   123.8  649.66   133.3  655.29   142.7  661.03   152.1  666.86
   161.5  672.77   170.9  678.17
#Mann= 3 , 0 , 0
       0      .1       0      74    .045       0      89      .1       0
Bank Sta=74,89
XS Rating Curve= 0 ,0
Exp/Cntr=0.3,0.1

Type RM Length L Ch R = 1 ,6275.1  ,262.4,259.9,257.6
XS GIS Cut Line= 4
     1740935.128      475393.482     1740910.823      475409.107
     1740850.059      475438.621     1740783.218      475500.253
#Sta/Elev= 23
       0   657.6     9.6  651.02    19.3  644.42    28.9  638.52    38.5  633.81
    48.2  631.01    49.7  630.87    57.8   630.1    64.7  630.16    67.5  630.19
    77.2  631.47    86.8   633.9    96.4  636.51   105.5  638.81   114.6  641.06
   123.7  643.58   132.8  646.36   141.9  649.06     151  652.75   160.1  657.45
   169.2  663.42   178.3  669.72   187.4  676.13
#Mann= 3 , 0 , 0
       0      .1       0    49.7    .045       0    67.5      .1       0
Bank Sta=49.7,67.5
XS Rating Curve= 0 ,0
Exp/Cntr=0.3,0.1

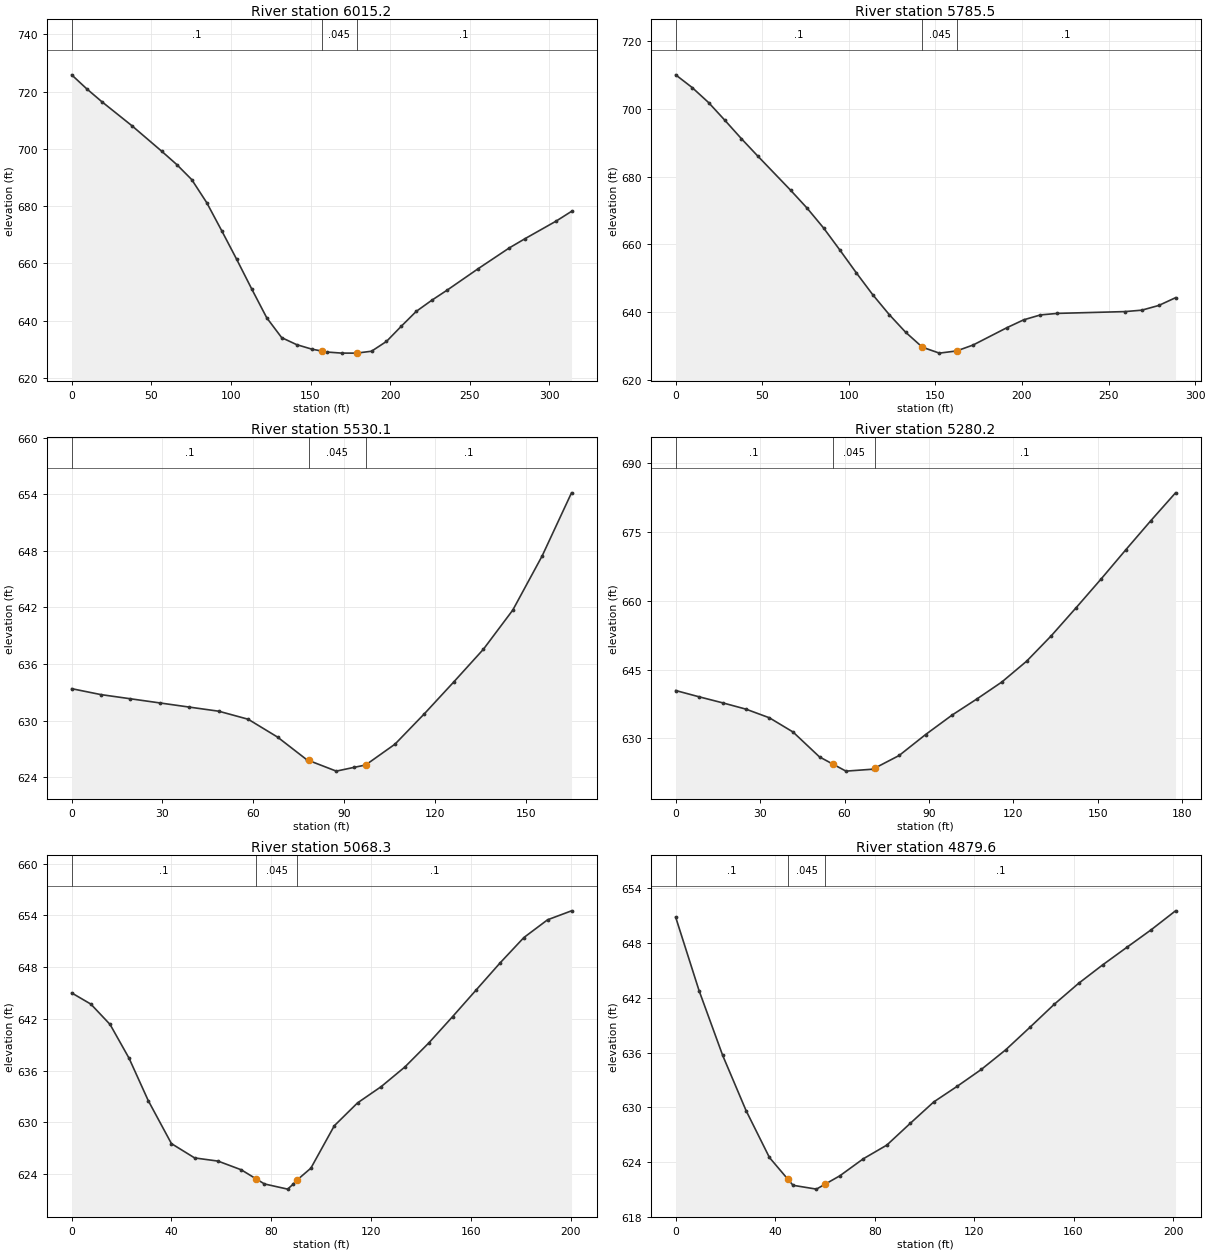
Type RM Length L Ch R = 1 ,6015.2  ,251,229.7,207.9
XS GIS Cut Line= 4
     1740876.533      475141.324     1740765.857      475193.829
     1740685.996      475243.308     1740639.989      475329.246
#Sta/Elev= 30
       0  725.83     9.4  720.98    18.8  716.52    37.7  708.13    56.5  699.19
      66  694.52    75.4  689.27    84.8  681.24    94.2  671.46   103.6  661.48
   113.1  651.08   122.5  641.05   131.9  634.11   141.3  631.67   150.7  630.12
     157  629.44   160.1   629.1   169.5  628.72   178.9  628.71   188.3  629.37
   197.7  632.79     207  638.09   216.4  643.28   226.2  647.18   235.9  650.73
   255.4  658.22   274.9  665.45   284.7  668.65   304.2  674.77   313.9  678.18
#Mann= 3 , 0 , 0
       0      .1       0     157    .045       0   178.9      .1       0
Bank Sta=157,178.9
XS Rating Curve= 0 ,0
Exp/Cntr=0.3,0.1

Type RM Length L Ch R = 1 ,5785.5  ,269.6,255.4,240.9
XS GIS Cut Line= 3
      1740614.38      474913.894     1740579.225      475041.919
     1740566.205      475197.301
#Sta/Elev= 26
       0  710.09     9.5  706.34      19   701.9    28.4  696.67    37.9  691.26
    47.4   686.1    66.4  675.99    75.9  670.71    85.4  664.86    94.8  658.35
   104.3  651.62   113.8  645.14   123.3  639.28   132.8  634.05   142.5  629.61
   152.3  627.87   162.3  628.52   171.8  630.27   191.2  635.36     201  637.71
   210.7  639.16   220.5  639.61   259.5  640.14   269.2  640.56     279  641.95
   288.7  644.24
#Mann= 3 , 0 , 0
       0      .1       0   142.5    .045       0   162.3      .1       0
Bank Sta=142.5,162.3
XS Rating Curve= 0 ,0
Exp/Cntr=0.3,0.1

Type RM Length L Ch R = 1 ,5530.1  ,244.7,249.9,253.8
XS GIS Cut Line= 2
      1740309.26      475103.551      1740394.33      475245.044
#Sta/Elev= 20
       0  633.38     9.7  632.75    19.4  632.31    29.1  631.87    38.8  631.43
    48.6  630.99    58.3  630.14      68  628.25    77.7  625.84    78.3  625.77
    87.4  624.64    93.3  625.04    97.1  625.29   106.8   627.5   116.5  630.72
   126.2  634.09     136  637.56   145.7  641.71   155.4  647.45   165.1  654.14
#Mann= 3 , 0 , 0
       0      .1       0    78.3    .045       0    97.1      .1       0
Bank Sta=78.3,97.1
XS Rating Curve= 0 ,0
Exp/Cntr=0.3,0.1

Type RM Length L Ch R = 1 ,5280.2  ,193.3,212,231.2
XS GIS Cut Line= 4
     1740120.024       475206.85     1740120.024      475248.517
     1740139.989      475301.468     1740153.878      475379.593
#Sta/Elev= 23
       0  640.46     8.3  639.09    16.7  637.77      25  636.39    33.3  634.51
    41.7  631.41    51.1  625.98    55.8  624.43    60.5  622.88      70   623.3
    70.8  623.55    79.4  626.29    88.8  630.86    98.3  635.14   107.1  638.65
   115.9  642.32   124.7  646.86   133.5  652.43   142.3  658.53   151.2  664.81
     160   671.2   168.8  677.48   177.6  683.57
#Mann= 3 , 0 , 0
       0      .1       0    55.8    .045       0    70.8      .1       0
Bank Sta=55.8,70.8
XS Rating Curve= 0 ,0
Exp/Cntr=0.3,0.1

Type RM Length L Ch R = 1 ,5068.3  ,207.8,188.6,168.9
XS GIS Cut Line= 4
      1739961.17      475180.808     1739946.413      475207.718
     1739906.482      475281.503     1739922.975      475365.704
#Sta/Elev= 26
       0  645.01     7.7  643.71    15.4  641.35      23  637.44    30.7  632.52
      40  627.53    49.3  625.87    58.7   625.5      68  624.49    73.9  623.45
    77.3  622.85    86.6  622.25    88.9  622.85   90.35   623.3    95.9  624.68
   105.3   629.6   114.6  632.25   124.1  634.14   133.6  636.42   143.2  639.21
   152.7  642.25   162.2  645.36   171.8   648.5   181.3  651.43   190.8  653.49
   200.4  654.53
#Mann= 3 , 0 , 0
       0      .1       0    73.9    .045       0   90.35      .1       0
Bank Sta=73.9,90.35
XS Rating Curve= 0 ,0
Exp/Cntr=0.3,0.1

Type RM Length L Ch R = 1 ,4879.6  ,220.9,229.7,238.7
XS GIS Cut Line= 3
     1739724.191      475186.885     1739764.121      475292.788
     1739768.461      475380.461
#Sta/Elev= 24
       0  650.85     9.4   642.8    18.9  635.69    28.3  629.64    37.7  624.49
    45.2  622.08    47.2  621.44    56.6  621.02    60.2  621.58      66  622.48
    75.4  624.34    84.9  625.85    94.3  628.23   103.8  630.59   113.2   632.3
   122.9  634.15   132.7   636.3   142.4  638.76   152.2  641.29     162  643.59
   171.7  645.62   181.4  647.54   191.2  649.47     201  651.55
#Mann= 3 , 0 , 0
       0      .1       0    45.2    .045       0    60.2      .1       0
Bank Sta=45.2,60.2
XS Rating Curve= 0 ,0
Exp/Cntr=0.3,0.1