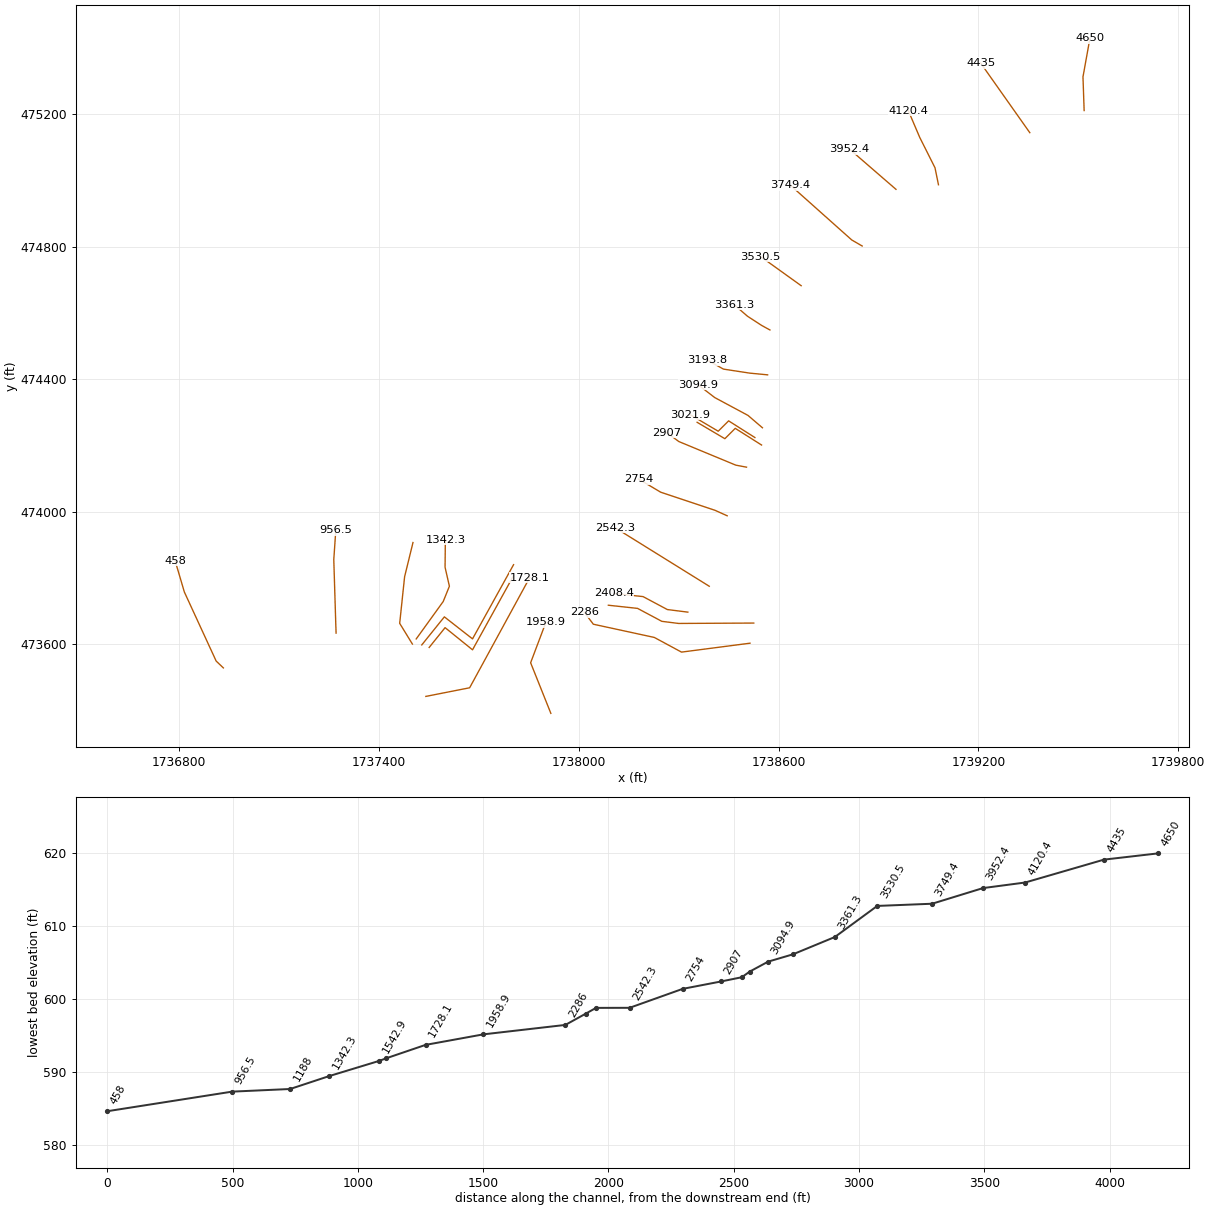
HEC-RAS study CROOKEDCK.prj: CROOKEDCK

--- CROOKEDCK.g01 (geometry) --- (continued)

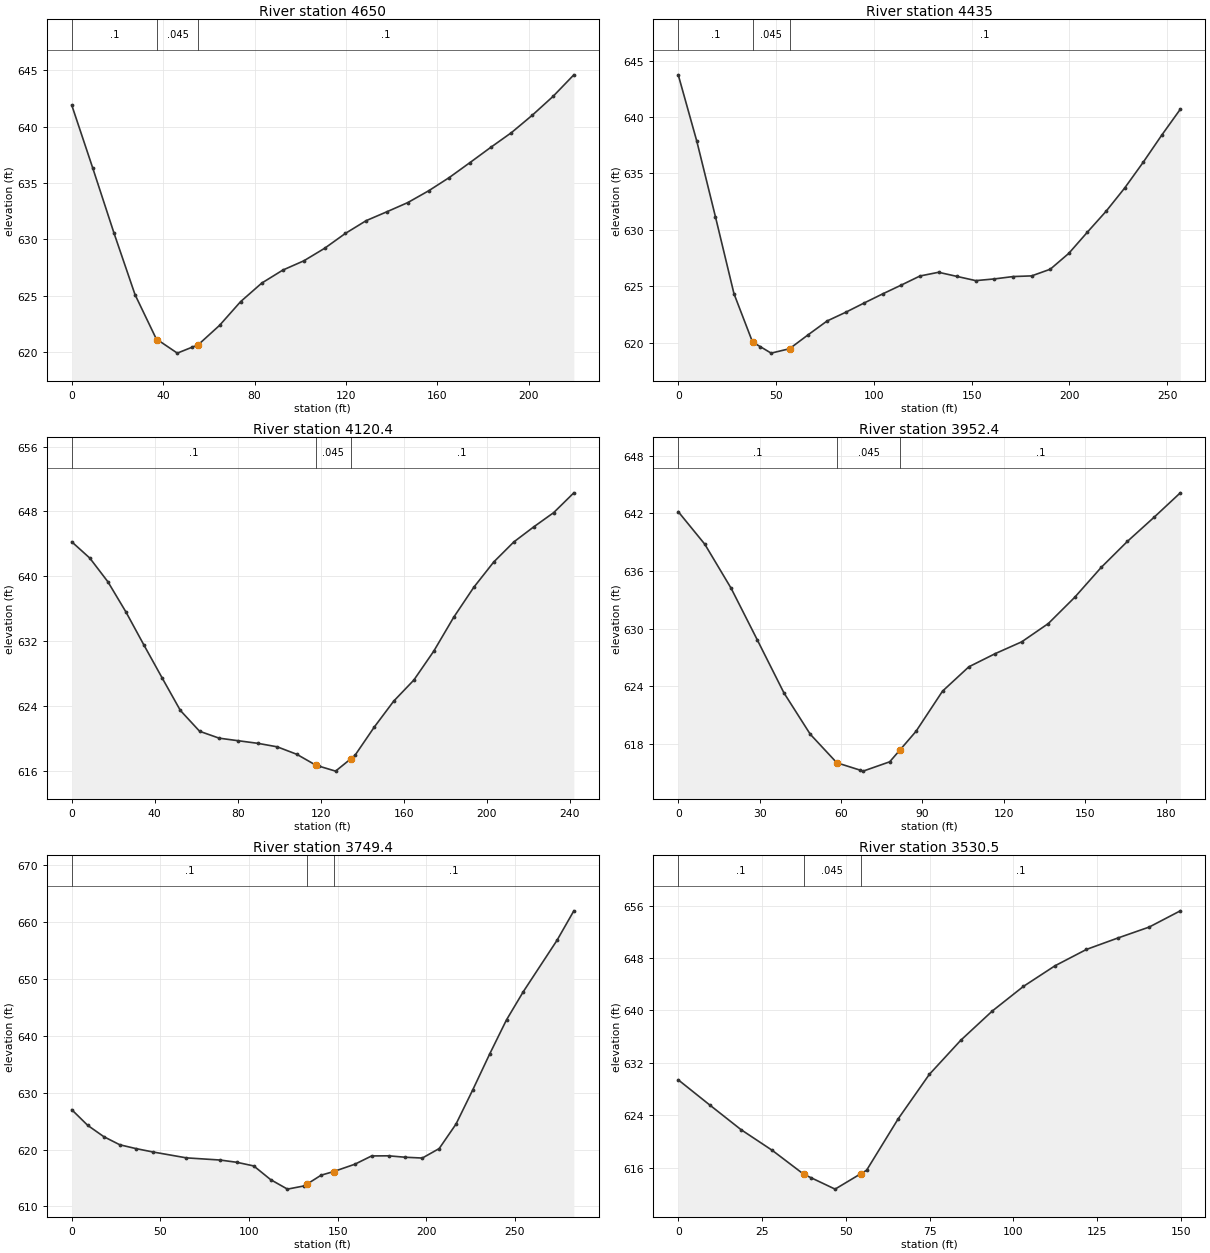
Type RM Length L Ch R = 1 ,4650    ,201.7,214.9,227.9
XS GIS Cut Line= 3
     1739517.593       475211.19     1739514.121      475312.753
     1739534.955      475429.072
#Sta/Elev= 27
       0  641.89     9.2  636.31    18.5  630.55    27.7   625.1      37  621.18
    37.5  621.11    46.2  619.92    52.5  620.43    55.4  620.67    64.7  622.38
    73.9  624.48    83.2  626.13    92.4  627.28   101.6   628.1   110.7  629.21
   119.8  630.53   128.9  631.66     138  632.45   147.1  633.26   156.2   634.3
   165.2  635.47   174.3   636.8   183.4  638.15   192.5  639.46   201.6     641
   210.7  642.67   219.8  644.58
#Mann= 3 , 0 , 0
       0      .1       0    37.5    .045       0    55.4      .1       0
Bank Sta=37.5,55.4
XS Rating Curve= 0 ,0
Exp/Cntr=0.3,0.1

Type RM Length L Ch R = 1 ,4435    ,317.8,314.6,310.8
XS GIS Cut Line= 2
     1739354.399       475144.35      1739206.83      475354.419
#Sta/Elev= 29
       0  643.75     9.5  637.86      19  631.18    28.5  624.34      38  620.05
    41.9  619.65    47.5  619.07    56.9  619.46    66.6  620.72    76.1  621.92
    85.6  622.69    95.1  623.52   104.6  624.33   114.1  625.11   123.6  625.91
   133.1  626.24   142.6  625.87   152.1   625.5   161.6  625.65   171.2  625.86
   180.7  625.92   190.2  626.51   199.7  627.92   209.2   629.8   218.7  631.64
   228.2   633.7   237.7  635.99   247.2   638.4   256.7   640.7
#Mann= 3 , 0 , 0
       0      .1       0      38    .045       0    56.9      .1       0
Bank Sta=38,56.9
XS Rating Curve= 0 ,0
Exp/Cntr=0.3,0.1

Type RM Length L Ch R = 1 ,4120.4  ,159.3,168,177
XS GIS Cut Line= 4
     1739080.093      474987.232     1739069.677      475038.447
      1739023.67      475130.461     1738989.816      475210.322
#Sta/Elev= 29
       0  644.25     8.7  642.24    17.4  639.32    26.1  635.59    34.8  631.49
    43.6  627.42    52.3  623.44    61.6  620.86      71  620.01    80.3  619.69
    89.7  619.37      99  618.94   108.4  618.02   117.7  616.66   119.3  616.54
   127.1  615.94   134.3  617.43   136.4  617.87   145.8   621.4   155.1  624.58
   164.8  627.18   174.4  630.75     184  634.93   193.7  638.64   203.3  641.76
     213  644.24   222.6   646.1   232.2  647.86   241.9   650.3
#Mann= 3 , 0 , 0
       0      .1       0   117.7    .045       0   134.3      .1       0
Bank Sta=117.7,134.3
XS Rating Curve= 0 ,0
Exp/Cntr=0.3,0.1

Type RM Length L Ch R = 1 ,3952.4  ,203.4,203.1,202.7
XS GIS Cut Line= 2
     1738952.489      474973.343     1738812.732      475094.871
#Sta/Elev= 22
       0  642.19     9.8   638.8    19.5  634.22    29.2  628.82      39  623.32
    48.7  619.02    58.5  616.05    66.9   615.3    68.2  615.18      78  616.15
    81.9  617.42    87.7  619.32    97.5  623.51   107.2  626.04     117  627.42
   126.7  628.64   136.5  630.54   146.2  633.26     156  636.38   165.7   639.1
   175.5   641.6   185.2  644.15
#Mann= 3 , 0 , 0
       0      .1       0    58.5    .045       0    81.9      .1       0
Bank Sta=58.5,81.9
XS Rating Curve= 0 ,0
Exp/Cntr=0.3,0.1

Type RM Length L Ch R = 1 ,3749.4  ,216.5,218.9,221.3
XS GIS Cut Line= 3
     1738850.927      474802.336     1738819.677      474820.565
     1738635.649      474985.496
#Sta/Elev= 29
       0  626.99       9  624.24    18.1  622.25    27.1  620.83    36.2  620.16
    45.7  619.57    64.7  618.53    83.7  618.15    93.2  617.75   102.7  617.11
   112.2  614.71   121.7  613.04   131.2  613.61   132.8  613.93   140.7  615.49
   147.8  616.13   159.7  617.41   169.2  618.87   178.8  618.89   188.2  618.64
   197.8   618.5   207.3  620.16   216.8  624.46   226.3   630.5   235.8  636.77
   245.3  642.77   254.8  647.73   273.8  656.74   283.3  661.92
#Mann= 3 , 0 , 0
       0      .1       0   132.8    .045       0   147.8      .1       0
Bank Sta=132.8,147.8
XS Rating Curve= 0 ,0
Exp/Cntr=0.3,0.1

Type RM Length L Ch R = 1 ,3530.5  ,167.9,169.2,170.3
XS GIS Cut Line= 2
     1738667.767      474682.544     1738546.239      474770.218
#Sta/Elev= 19
       0  629.42     9.4  625.58    18.7  621.83    28.1  618.64    37.5  614.99
    39.5  614.51    46.8  612.74    54.5   615.1    56.2  615.62    65.6  623.45
    74.9  630.24    84.3  635.46    93.7  639.92     103  643.68   112.4  646.82
   121.8  649.32   131.1  651.05   140.5  652.73   149.8  655.21
#Mann= 3 , 0 , 0
       0      .1       0    37.5    .045       0    54.5      .1       0
Bank Sta=37.5,54.5
XS Rating Curve= 0 ,0
Exp/Cntr=0.3,0.1

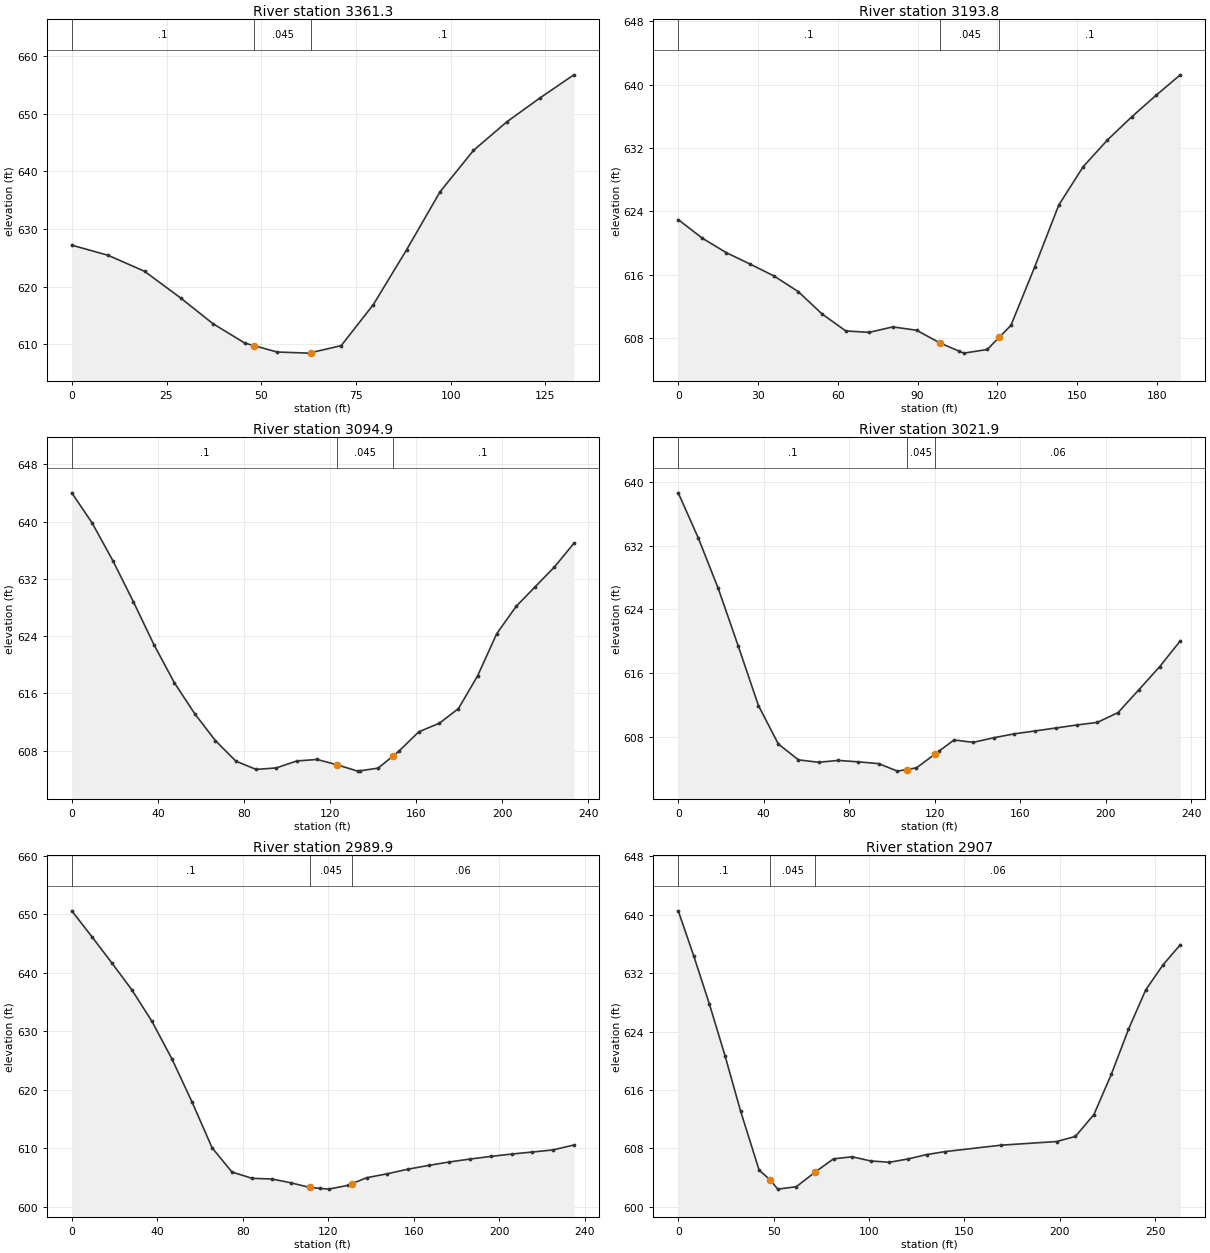
Type RM Length L Ch R = 1 ,3361.3  ,157.8,167.4,176.2
XS GIS Cut Line= 4
     1738574.017      474548.864     1738548.843      474562.753
     1738506.309      474590.531     1738466.378      474625.253
#Sta/Elev= 18
       0  627.21     9.6  625.45    19.2  622.68    28.8  618.02    37.2  613.62
    45.7  610.22    48.2  609.77    54.2  608.68    62.6  608.49    63.2  608.58
    71.1  609.79    79.6  616.92    88.4  626.45    97.2  636.47     106  643.63
   114.8  648.58   123.6  652.75   132.5  656.74
#Mann= 3 , 0 , 0
       0      .1       0    48.2    .045       0    63.2      .1       0
Bank Sta=48.2,63.2
XS Rating Curve= 0 ,0
Exp/Cntr=0.3,0.1

Type RM Length L Ch R = 1 ,3193.8  ,106.9,98.9,91.8
XS GIS Cut Line= 4
     1738567.073      474413.447     1738513.253      474418.656
      1738434.26      474430.808     1738386.517      474457.718
#Sta/Elev= 24
       0  622.97       9  620.64      18  618.81      27  617.36      36  615.86
    45.1  613.89    54.1  611.06      63  608.92    71.8  608.74    80.7  609.43
    89.6  609.01    98.5  607.39   105.7  606.36   107.4  606.12   116.2  606.58
   120.7  608.12   125.1  609.62     134  616.96   143.1  624.81   152.3  629.66
   161.4  633.02   170.5  635.93   179.7  638.66   188.8  641.24
#Mann= 3 , 0 , 0
       0      .1       0    98.5    .045       0   120.7      .1       0
Bank Sta=98.5,120.7
XS Rating Curve= 0 ,0
Exp/Cntr=0.3,0.1

Type RM Length L Ch R = 1 ,3094.9  ,49.6,73,101.8
XS GIS Cut Line= 4
     1738551.448      474253.725     1738508.045      474291.051
     1738408.218      474344.871     1738358.739      474383.065
#Sta/Elev= 28
       0  644.02     9.5  639.79    19.1  634.53    28.6  628.81    38.2  622.78
    47.7  617.45    57.2  613.11    66.7  609.39    76.2  606.52    85.6  605.36
      95  605.57   104.5  606.54     114  606.75   123.4  605.99   132.8  605.12
     134  605.17   142.3  605.54     149  607.18   151.8  607.87   161.2  610.62
   170.7  611.81   179.6  613.86   188.5  618.44   197.4  624.34   206.4  628.15
   215.3  630.91   224.2  633.66   233.2  636.96
#Mann= 3 , 0 , 0
       0      .1       0   123.4    .045       0     149      .1       0
Bank Sta=123.4,149
XS Rating Curve= 0 ,0
Exp/Cntr=0.3,0.1

Type RM Length L Ch R = 1 ,3021.9  ,25.9,32,16.3
XS GIS Cut Line= 4
     1738528.878      474224.211     1738449.885      474274.558
     1738418.635      474243.308     1738335.302      474292.788
#Sta/Elev= 28
       0   638.6     9.4  632.94    18.7  626.64    28.1   619.4    37.5  611.98
    46.8  607.17    56.2  605.18    65.6  604.88    74.9  605.11    84.3  604.93
    93.7  604.71   102.5  603.77   106.8  603.97   111.4  604.18   120.2  605.93
   121.8  606.25     129  607.67   137.9  607.37   147.6  607.95   157.2  608.44
   166.9   608.8   176.6  609.17   186.3  609.54     196  609.87   205.7   611.1
   215.4  613.95   225.1  616.83   234.8  620.08
#Mann= 3 , 0 , 0
       0      .1       0   106.8    .045       0   120.2     .06       0
Bank Sta=106.8,120.2
XS Rating Curve= 0 ,0
Exp/Cntr=0.3,0.1

Type RM Length L Ch R = 1 ,2989.9  ,110.2,82.9,71.8
XS GIS Cut Line= 4
     1738548.843      474201.642      1738469.85      474251.989
       1738438.6      474220.739     1738355.267      474270.218
#Sta/Elev= 28
       0  650.61     9.4  646.19    18.7  641.72    28.1  637.09    37.5  631.69
    46.8   625.3    56.2  617.94    65.6  610.08    74.9  605.92    84.3  604.84
    93.7  604.72   102.5  604.07   111.4  603.27   115.9  603.13   120.2  602.99
     129  603.63   130.9  603.91   137.9  604.94   147.6  605.62   157.2   606.4
   166.9  607.05   176.6  607.64   186.3  608.14     196  608.59   205.7  608.99
   215.4  609.34   225.1   609.7   234.8  610.54
#Mann= 3 , 0 , 0
       0      .1       0   111.4    .045       0   130.9     .06       0
Bank Sta=111.4,130.9
XS Rating Curve= 0 ,0
Exp/Cntr=0.3,0.1

Type RM Length L Ch R = 1 ,2907    ,151.5,153.1,154.7
XS GIS Cut Line= 4
     1738503.705      474134.801     1738471.586      474140.878
      1738300.58      474212.058     1738264.121      474238.968
#Sta/Elev= 26
       0  640.53     8.2   634.3    16.3  627.79    24.5   620.7    32.7  613.09
    42.4  605.02    48.1   603.7    52.2  602.41    61.9  602.74    71.8  604.75
    81.4  606.56    91.2  606.84   100.9  606.27   110.7  606.09   120.4  606.54
   130.2  607.14   139.9  607.55   169.2  608.43   198.4  608.93   208.2  609.63
   217.9  612.62     227  618.12     236  624.28   245.1  629.72   254.2  633.15
   263.2  635.89
#Mann= 3 , 0 , 0
       0      .1       0    48.1    .045       0    71.8     .06       0
Bank Sta=48.1,71.8
XS Rating Curve= 0 ,0
Exp/Cntr=0.3,0.1

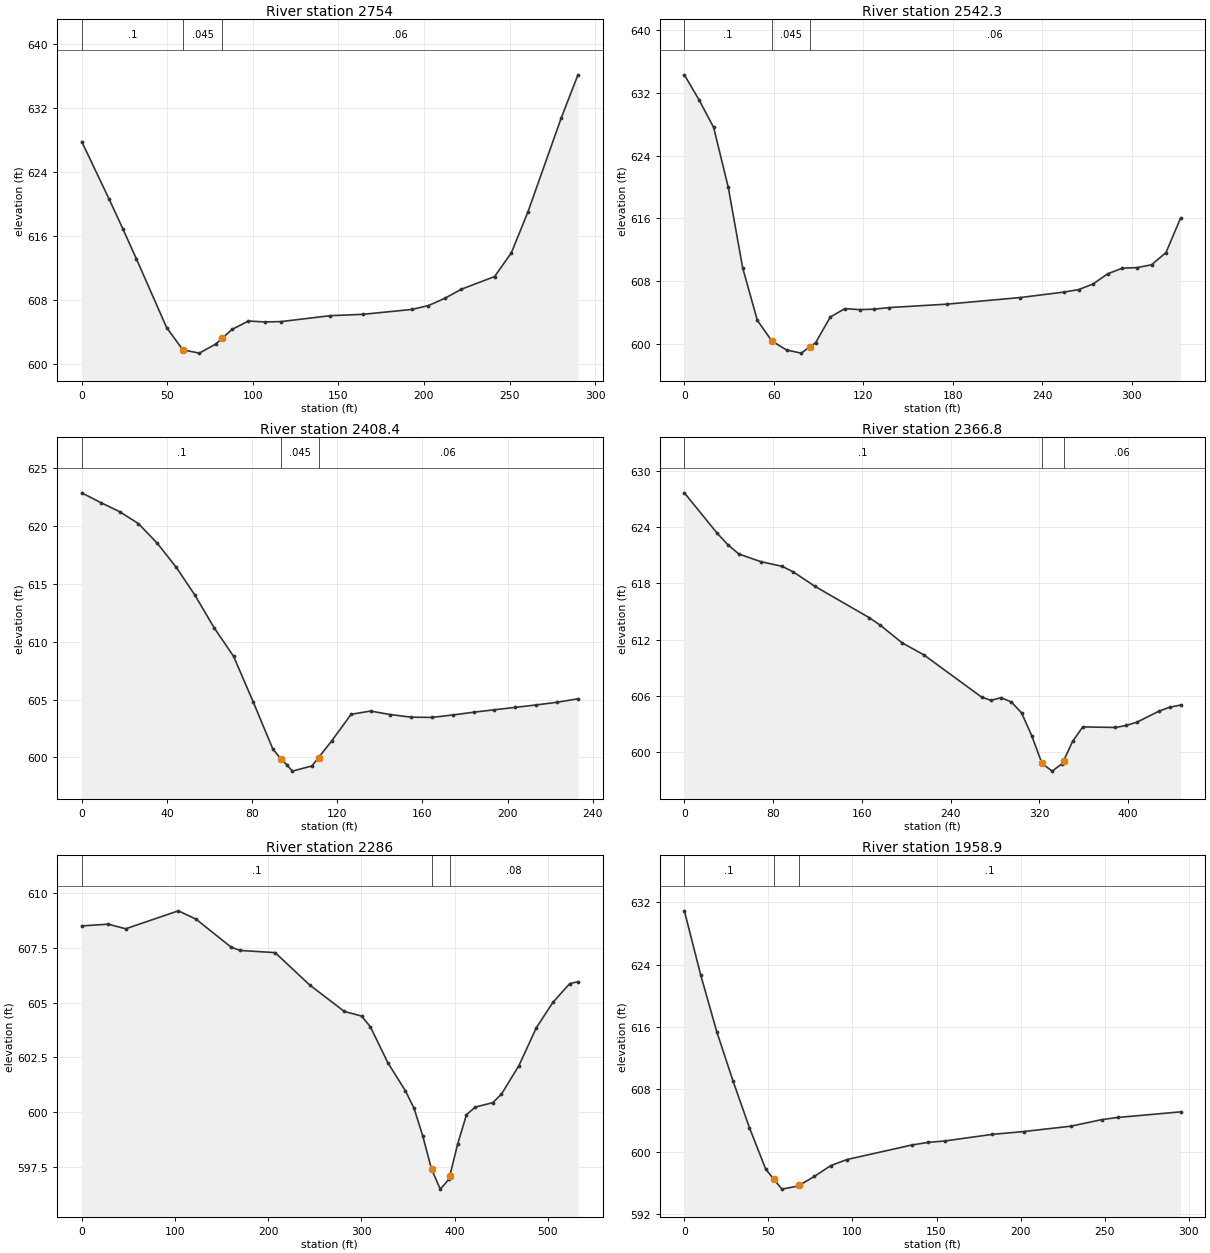
Type RM Length L Ch R = 1 ,2754    ,217,211.7,206.4
XS GIS Cut Line= 4
     1738445.545        473988.1     1738409.086      474004.593
     1738245.892      474059.281     1738179.052      474099.211
#Sta/Elev= 24
       0  627.84      16  620.65      24  616.95      32  613.16    49.6   604.6
    59.1  601.81    68.7   601.4    78.3  602.53    82.1  603.26    87.8  604.36
    97.4  605.41     107   605.3   116.5  605.34   145.2  606.08   164.3  606.25
     193  606.86   202.6  607.34   212.1  608.24   221.9  609.39   241.3  610.97
   251.1  613.95   260.8  619.07   280.3  630.83     290  636.18
#Mann= 3 , 0 , 0
       0      .1       0    59.1    .045       0    82.1     .06       0
Bank Sta=59.1,82.1
XS Rating Curve= 0 ,0
Exp/Cntr=0.3,0.1

Type RM Length L Ch R = 1 ,2542.3  ,131.9,133.9,135.5
XS GIS Cut Line= 2
     1738391.725      473775.426     1738109.607      473951.642
#Sta/Elev= 27
       0  634.32     9.8  631.13    19.6  627.62    29.4  619.97    39.1  609.67
    48.9  602.99    58.7  600.35    68.5  599.21    78.3  598.81    83.9  599.58
      88  600.15    97.8  603.42   107.6  604.49   117.4  604.36   127.2  604.42
     137  604.62   176.1  605.06     225   605.9   254.4   606.6   264.2  606.91
   273.9  607.63   283.7  608.93   293.5  609.65   303.3  609.72   313.1  610.08
   322.8  611.64   332.6  616.06
#Mann= 3 , 0 , 0
       0      .1       0    58.7    .045       0    83.9     .06       0
Bank Sta=58.7,83.9
XS Rating Curve= 0 ,0
Exp/Cntr=0.3,0.1

Type RM Length L Ch R = 1 ,2408.4  ,41.7,41.6,41.7
XS GIS Cut Line= 4
     1738327.489      473697.301     1738265.857      473705.114
     1738192.941      473744.176     1738105.267      473753.725
#Sta/Elev= 29
       0  622.89     8.9  622.05    17.8  621.26    26.6  620.23    35.5  618.52
    44.4  616.44    53.2  614.02    62.1  611.23    71.3  608.74    80.5   604.8
    89.7  600.73   93.67  599.82    96.2  599.37    98.9   598.8   108.1  599.25
   111.2  599.97   117.3   601.4   126.5  603.72   135.6     604   144.8   603.7
   154.6  603.47   164.4  603.45   174.2  603.66     184   603.9   193.8  604.11
   203.6  604.32   213.4  604.53   223.2  604.76     233  605.06
#Mann= 3 , 0 , 0
       0      .1       0   93.67    .045       0   111.2     .06       0
Bank Sta=93.67,111.2
XS Rating Curve= 0 ,0
Exp/Cntr=0.3,0.1

Type RM Length L Ch R = 1 ,2366.8  ,74.1,80.8,87.5
XS GIS Cut Line= 5
     1738525.406      473664.315     1738299.673      473663.146
     1738249.364      473669.524     1738176.448      473708.586
     1738088.774      473718.135
#Sta/Elev= 30
       0  627.63    29.4  623.35    39.3  622.09    49.1  621.12    68.7  620.31
    88.3   619.8    98.2  619.21   117.8  617.67   166.8  614.33   176.7  613.53
   196.3  611.66   215.9  610.38     268  605.88   276.4  605.54   285.6  605.82
   294.8  605.36     304   604.2   313.2  601.77   322.4  598.82   331.6     598
   340.8  598.81   341.9  599.09     350  601.16   359.2  602.71   388.6  602.65
   398.4  602.86   408.2  603.22   427.8  604.38   437.6  604.81   447.4  605.03
#Mann= 3 , 0 , 0
       0      .1       0   322.4    .045       0   341.9     .06       0
Bank Sta=322.4,341.9
XS Rating Curve= 0 ,0
Exp/Cntr=0.3,0.1

Type RM Length L Ch R = 1 ,2286    ,350.1,327.1,304.2
XS GIS Cut Line= 5
     1738514.121      473603.551     1738308.392      473576.642
     1738226.795      473620.913     1738043.635      473660.843
     1738016.725      473696.433
#Sta/Elev= 30
       0   608.5    28.3  608.58    47.2  608.37   103.7  609.19   122.6  608.81
   160.3  607.53   169.8  607.38   207.5  607.28   244.6   605.8   281.8  604.59
   300.3  604.38   309.7  603.89   328.4  602.25   347.2  600.97   356.6  600.16
   365.9   598.9   375.3  597.38   384.7  596.47     394  596.92     395  597.09
   403.4  598.54   412.8  599.87   422.2  600.22   440.9  600.42   450.3  600.81
     469  602.11   487.8  603.85   505.6  605.01   523.5  605.86   532.4  605.95
#Mann= 3 , 0 , 0
       0      .1       0   375.3    .045       0     395     .08       0
Bank Sta=375.3,395
XS Rating Curve= 0 ,0
Exp/Cntr=0.3,0.1

Type RM Length L Ch R = 1 ,1958.9  ,251.6,230.8,210.1
XS GIS Cut Line= 3
     1737916.031      473391.746     1737855.267      473544.524
     1737901.274      473666.919
#Sta/Elev= 22
       0  630.91     9.7  622.68    19.3  615.37      29  609.03    38.7  603.07
    48.4  597.74    53.3  596.43      58  595.18    67.7  595.58    68.3  595.66
    77.4  596.82      87  598.19    96.7  598.98   135.4  600.85   145.1  601.18
   154.8  601.36   183.1  602.21   201.8  602.57   229.8  603.26   248.5  604.11
   257.8  604.38   295.2   605.1
#Mann= 3 , 0 , 0
       0      .1       0    53.3    .045       0    68.3      .1       0
Bank Sta=53.3,68.3
XS Rating Curve= 0 ,0
Exp/Cntr=0.3,0.1

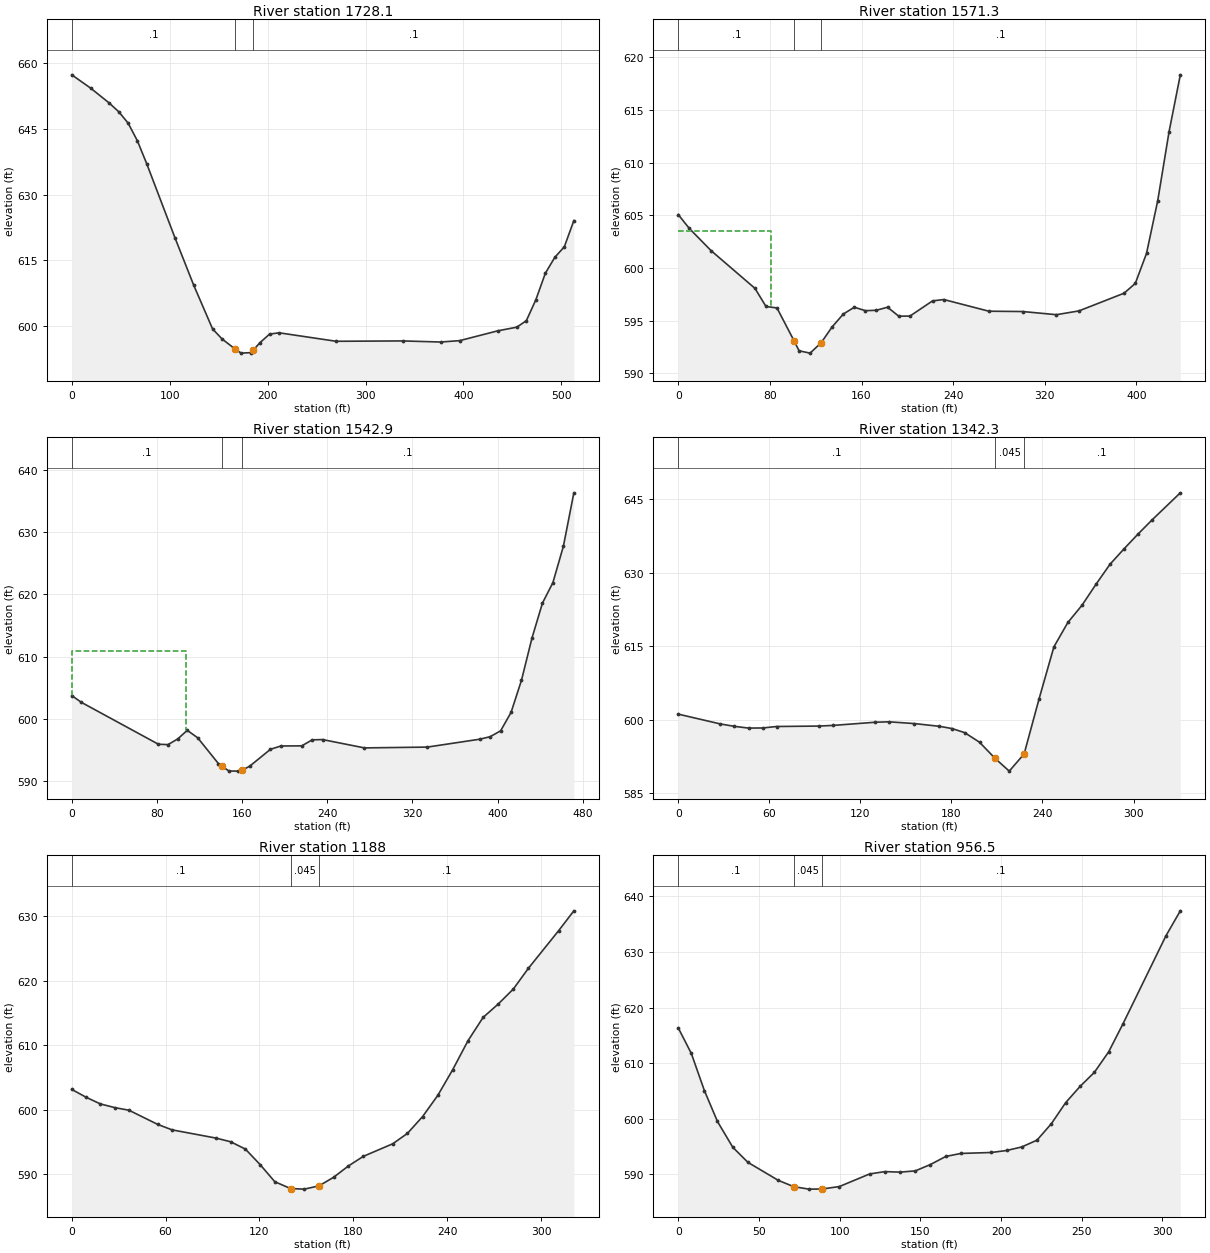
Type RM Length L Ch R = 1 ,1728.1  ,198.2,156.8,113.3
XS GIS Cut Line= 3
     1737540.597      473442.961     1737672.107      473469.003
     1737852.661      473801.828
#Sta/Elev= 30
       0   657.4    19.2  654.37    38.3  650.94    47.9  648.97    57.5  646.37
      67  642.31    76.6  637.03   105.3  620.17   124.5  609.29   143.8  599.27
   153.5  596.98     167  594.64   172.9  593.74   182.6  593.85  185.47  594.46
   192.3  596.16     202  598.09   211.7  598.39     270  596.45     338  596.53
   376.8  596.28   396.2   596.6     435  598.84   454.5  599.68   464.2  601.16
   473.9  605.94   483.6  612.02   493.3  615.66     503  618.07   512.7  624.05
#Mann= 3 , 0 , 0
       0      .1       0     167    .045       0  185.47      .1       0
Bank Sta=167,185.47
XS Rating Curve= 0 ,0
Exp/Cntr=0.3,0.1

Type RM Length L Ch R = 1 ,1571.3  ,26.9,28.4,30
XS GIS Cut Line= 4
     1737550.578      473590.716     1737598.404      473650.488
     1737680.788      473583.586     1737804.052      473807.544
#Sta/Elev= 30
       0  605.07     9.6  603.76    28.7  601.64      67  598.06    76.6  596.34
    86.2   596.2   101.3  593.04   105.5  592.13   115.1  591.91   124.8   592.9
   134.4  594.41   144.1  595.62   153.7  596.27   163.4  595.94     173  595.98
   182.7  596.27   192.5  595.42   202.3  595.43     222  596.87   231.8     597
   271.2  595.89   300.7  595.86   330.2  595.56   349.8  595.92   389.2   597.6
     399  598.53   408.8  601.38   418.6   606.4   428.5  612.95   438.3  618.34
#Mann= 3 , 0 , 0
       0      .1       0   101.3    .045       0   124.8      .1       0
#XS Ineff= 2 , 0
            80.6  603.55
Permanent Ineff=
       F       F
Bank Sta=101.3,124.8
XS Rating Curve= 0 ,0
Exp/Cntr=0.3,0.1

Type RM Length L Ch R = 1 ,1542.9  ,140.8,200.6,260
XS GIS Cut Line= 4
     1737528.356      473598.355     1737596.218       473683.02
     1737680.788      473616.572     1737804.052      473840.531
#Sta/Elev= 30
       0  603.72       9  602.63    81.4  595.88    90.4  595.82    99.5  596.73
   108.5  598.12   118.3  596.92   137.8  592.76   141.2  592.35   147.6  591.57
   156.2  591.55  160.32  591.72   167.2  592.35   186.7  595.07   196.5   595.6
   216.1  595.62   225.9  596.59   235.7  596.63     275  595.29     334  595.42
   383.2  596.69     393  597.09   402.9  598.04   412.7     601   422.5  606.18
   432.4     613   442.2  618.61     452   621.9   461.9  627.78   471.7  636.37
#Mann= 3 , 0 , 0
       0      .1       0   141.2    .045       0  160.32      .1       0
#XS Ineff= 2 , 0
          107.62  610.92
Permanent Ineff=
       F       F
Bank Sta=141.2,160.32
XS Rating Curve= 0 ,0
Exp/Cntr=0.3,0.1

Type RM Length L Ch R = 1 ,1342.3  ,166.2,154.4,143
XS GIS Cut Line= 5
     1737511.689      473616.411     1737592.722      473729.279
     1737611.343      473775.426     1737598.323      473832.718
     1737599.191      473916.051
#Sta/Elev= 28
       0  601.11    27.8   599.1      37  598.61    46.3  598.26    55.6  598.28
    64.8  598.58    92.6  598.67   101.9   598.8   129.7  599.45   138.9  599.54
   155.5  599.18   172.1  598.62   180.4  598.16   188.7  597.33   198.5  595.37
   208.7  592.08   218.1  589.46   227.9  592.98   237.7  604.18   247.5  614.85
   256.7  619.84     266  623.35   275.2  627.63   284.5  631.75   293.8  634.92
     303  637.93   312.3  640.84   330.8  646.34
#Mann= 3 , 0 , 0
       0      .1       0   208.7    .045       0   227.9      .1       0
Bank Sta=208.7,227.9
XS Rating Curve= 0 ,0
Exp/Cntr=0.3,0.1

Type RM Length L Ch R = 1 ,1188    ,221.1,231.4,240.6
XS GIS Cut Line= 4
     1737500.232      473600.947     1737462.038      473663.447
     1737476.795      473804.072     1737501.968      473907.371
#Sta/Elev= 30
       0  603.17     9.2  601.95    18.3  600.92    27.5  600.35    36.6  599.94
    54.9  597.75    64.1   596.9    92.1  595.63   101.5  595.06     111  593.92
   120.4  591.52   129.8  588.86   139.9   587.8   148.7  587.71   158.1  588.22
   167.5  589.56   176.9  591.31   186.4  592.79   205.2  594.74   214.6  596.35
   224.3  598.96     234  602.24   243.6  606.25   253.3  610.71     263  614.34
   272.6   616.4   282.3  618.73     292  621.97   311.3  627.79     321  630.86
#Mann= 3 , 0 , 0
       0      .1       0   139.9    .045       0   158.1      .1       0
Bank Sta=139.9,158.1
XS Rating Curve= 0 ,0
Exp/Cntr=0.3,0.1

Type RM Length L Ch R = 1 ,956.5   ,491.2,498.5,499.8
XS GIS Cut Line= 4
     1737271.066      473633.933     1737270.198      473658.239
     1737264.121      473856.156     1737270.198      473944.697
#Sta/Elev= 30
       0  616.36     8.1  611.76    16.2  605.08    24.3  599.52    33.8  594.88
    43.2  592.16      62  588.93    71.5   587.8    80.9  587.35      89  587.37
    99.8  587.81   118.6  590.08     128   590.5   137.5  590.41   146.9  590.63
   156.3  591.78   165.8  593.23   175.2  593.77     194  593.94   203.5   594.3
   212.9  594.94   222.3  596.16   231.2  599.12   240.1  602.92     249  605.83
   257.8  608.34   266.7  612.04   275.6   617.1   302.2  632.92   311.1  637.41
#Mann= 3 , 0 , 0
       0      .1       0    71.5    .045       0      89      .1       0
Bank Sta=71.5,89
XS Rating Curve= 0 ,0
Exp/Cntr=0.3,0.1

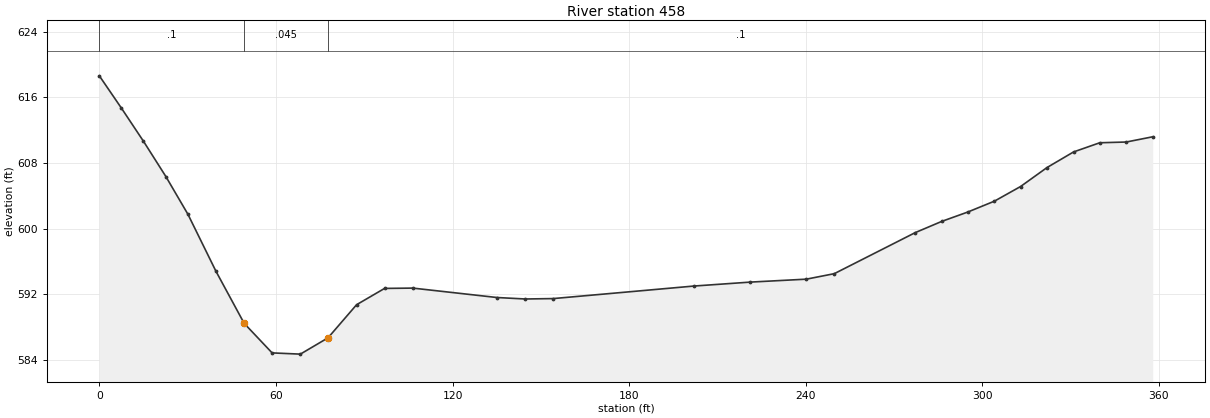
Type RM Length L Ch R = 1 ,458     ,98.1,95.8,93.5
XS GIS Cut Line= 4
     1736932.524      473528.899     1736910.823      473549.732
     1736815.336      473758.065     1736787.559      473852.683
#Sta/Elev= 30
       0  618.64     7.5   614.7      15  610.65    22.6  606.35    30.1  601.74
    39.6   594.8    49.2  588.43    58.7  584.82    68.3  584.67    77.7  586.66
    87.4   590.7    96.9  592.69   106.5  592.73   135.1  591.58   144.7   591.4
   154.2  591.45     202  592.98   221.1  593.46   240.2  593.82   249.7  594.49
   277.2   599.5   286.2  600.87   295.1  602.02   304.1  603.34     313  605.13
     322  607.45     331  609.35   339.9  610.47   348.9  610.56   357.9   611.2
#Mann= 3 , 0 , 0
       0      .1       0    49.2    .045       0    77.7      .1       0
Bank Sta=49.2,77.7
XS Rating Curve= 0 ,0
Exp/Cntr=0.3,0.1