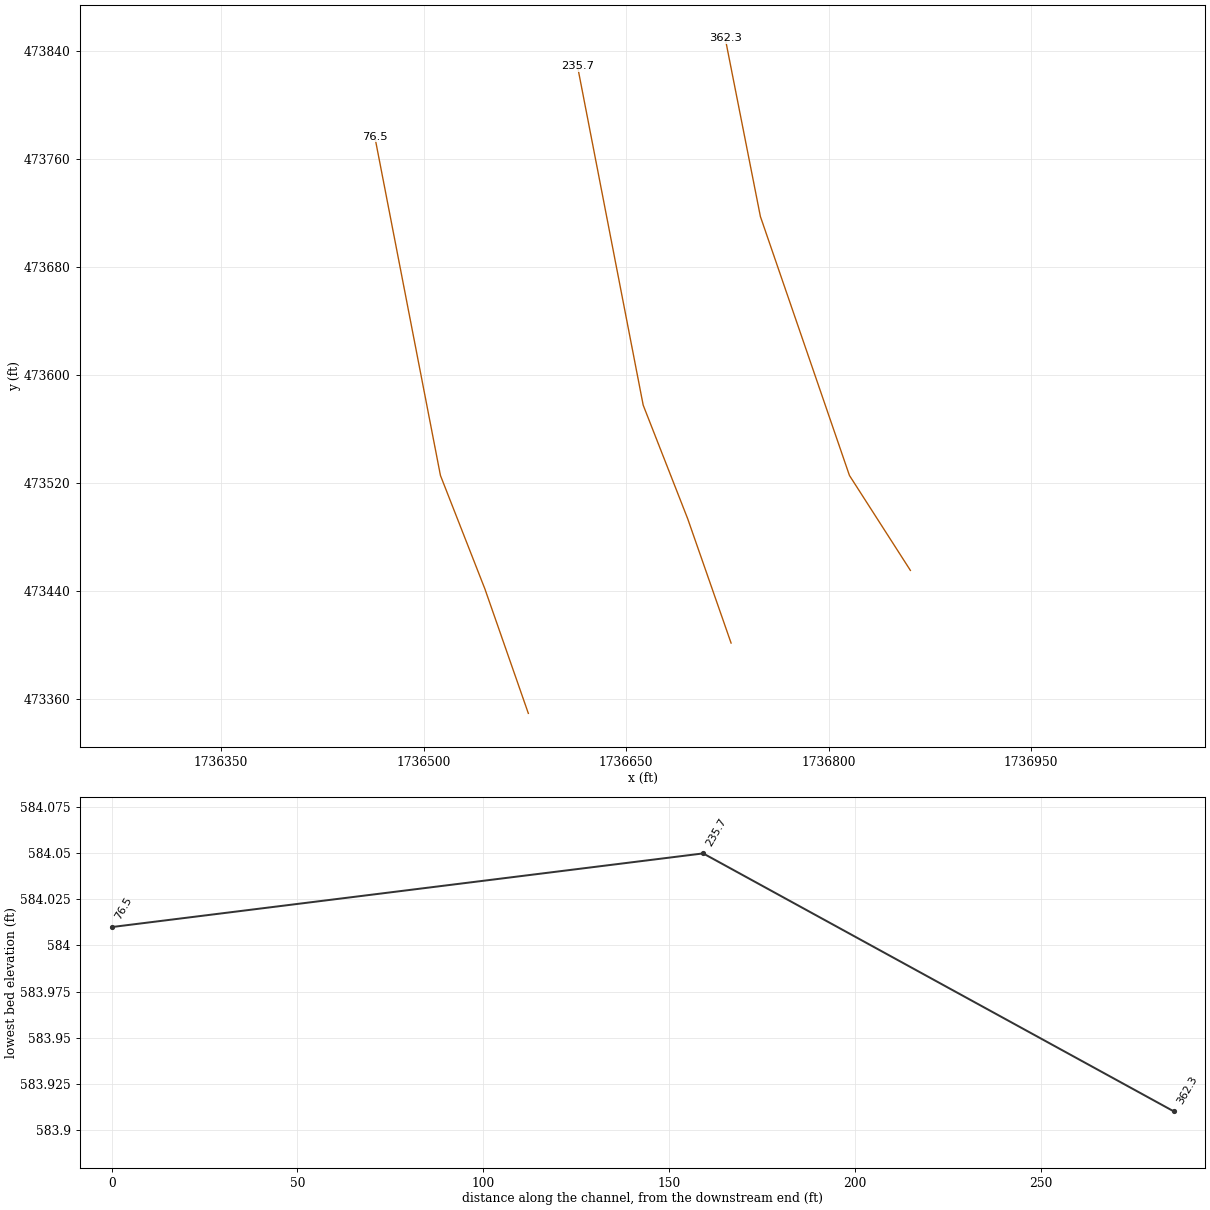
HEC-RAS study CROOKEDCK.prj: CROOKEDCK

--- CROOKEDCK.g01 (geometry) --- (continued)

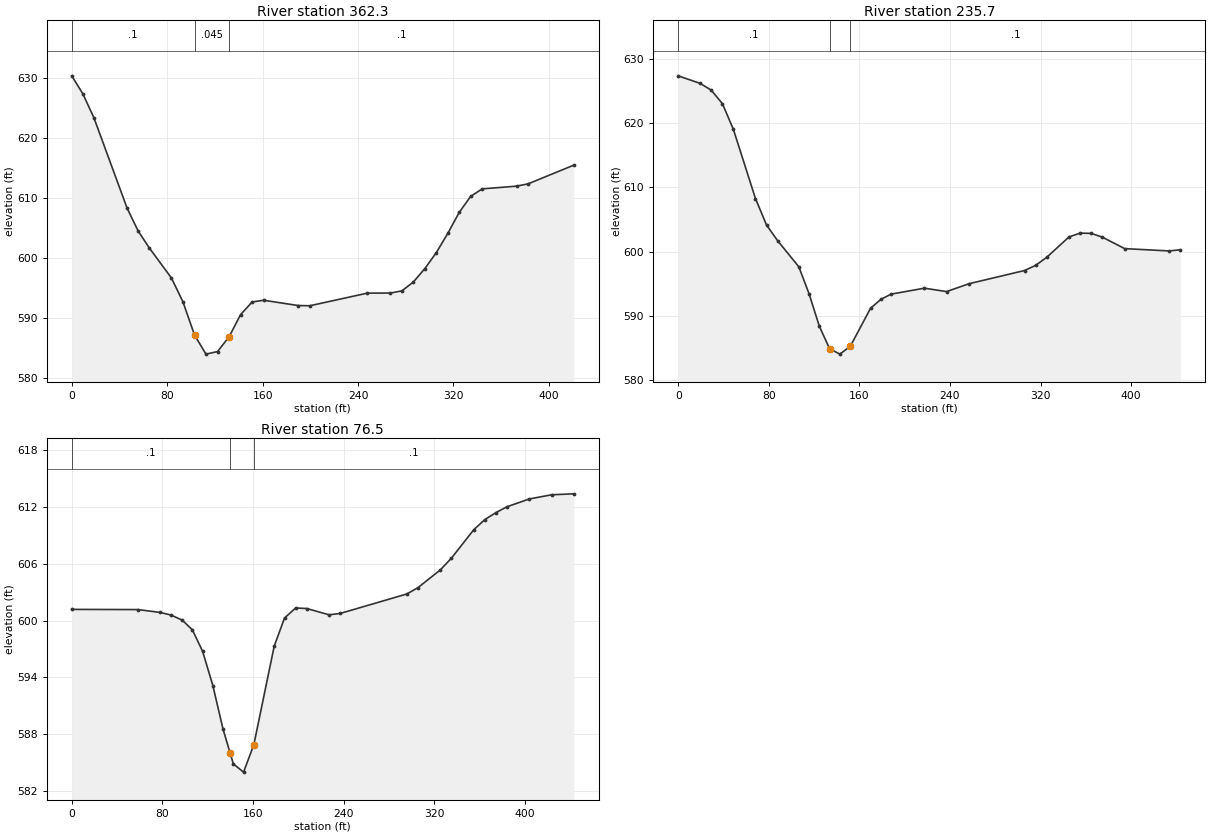
Type RM Length L Ch R = 1 ,362.3   ,125.6,126.6,127.5
XS GIS Cut Line= 4
     1736860.475      473455.114     1736815.336      473525.426
     1736749.364      473717.267     1736723.323      473849.211
#Sta/Elev= 30
       0  630.35     9.3  627.34    18.6  623.33    46.4  608.26    55.7  604.44
      65  601.63    83.6   596.6    93.2  592.64   102.9   587.1   112.5  583.91
   122.2  584.34   131.9  586.81   141.5   590.5   151.2  592.61   160.8   592.9
   189.8  592.02   199.5  591.98   247.8  594.09   267.1   594.1   276.8  594.47
   286.4  595.95     296  598.19   305.6  600.85   315.2  604.05   324.8  607.56
   334.4  610.23   344.1  611.49   372.9  611.94   382.5  612.32   420.9  615.45
#Mann= 3 , 0 , 0
       0      .1       0   102.9    .045       0   131.9      .1       0
Bank Sta=102.9,131.9
XS Rating Curve= 0 ,0
Exp/Cntr=0.3,0.1

Type RM Length L Ch R = 1 ,235.7   ,159.1,159.2,159.2
XS GIS Cut Line= 4
     1736727.663      473401.294     1736695.545      473493.308
     1736662.559       473577.51     1736613.948      473828.378
#Sta/Elev= 30
       0  627.39    19.5   626.2    29.2  625.15      39  623.06    48.7  619.05
    68.2  608.28      78  604.15    87.7  601.73   106.5  597.65   115.5  593.47
   124.6   588.4   133.6  584.91   142.7  584.05     152  585.28   169.8  591.18
   178.8  592.56   187.9  593.39   217.4  594.32     237  593.79   256.7  595.01
   305.8  597.07   315.7  597.88   325.5  599.14   345.1   602.3     355   602.9
   364.8  602.85   374.6  602.26   394.3  600.48   433.6  600.12   443.4   600.3
#Mann= 3 , 0 , 0
       0      .1       0   133.6    .045       0     152      .1       0
Bank Sta=133.6,152
XS Rating Curve= 0 ,0
Exp/Cntr=0.3,0.1

Type RM Length L Ch R = 1 ,76.5    ,77.1,76.5,76
XS GIS Cut Line= 4
     1736577.489      473349.211     1736545.371      473441.225
     1736512.385      473525.426     1736463.774      473776.294
#Sta/Elev= 30
       0  601.19    58.5  601.17      78  600.87    87.7  600.59    97.5  600.06
   106.5  599.03   115.5  596.78   124.6  593.15   133.6  588.54   139.8  586.05
   142.7  584.88   151.7  584.01   160.8  586.91   178.8  597.32   187.9  600.28
   197.7  601.34   207.6  601.28   227.2  600.62     237  600.76     296  602.82
   305.8  603.49   325.5  605.36   335.3   606.6     355   609.6   364.8  610.67
   374.6  611.41   384.5  612.03   404.1  612.85   423.8  613.29   443.4  613.39
#Mann= 3 , 0 , 0
       0      .1       0   139.8    .045       0   160.8      .1       0
Bank Sta=139.8,160.8
XS Rating Curve= 0 ,0
Exp/Cntr=0.3,0.1

Chan Stop Cuts=-1
Use User Specified Reach Order=0
Composite Channel Slope=5